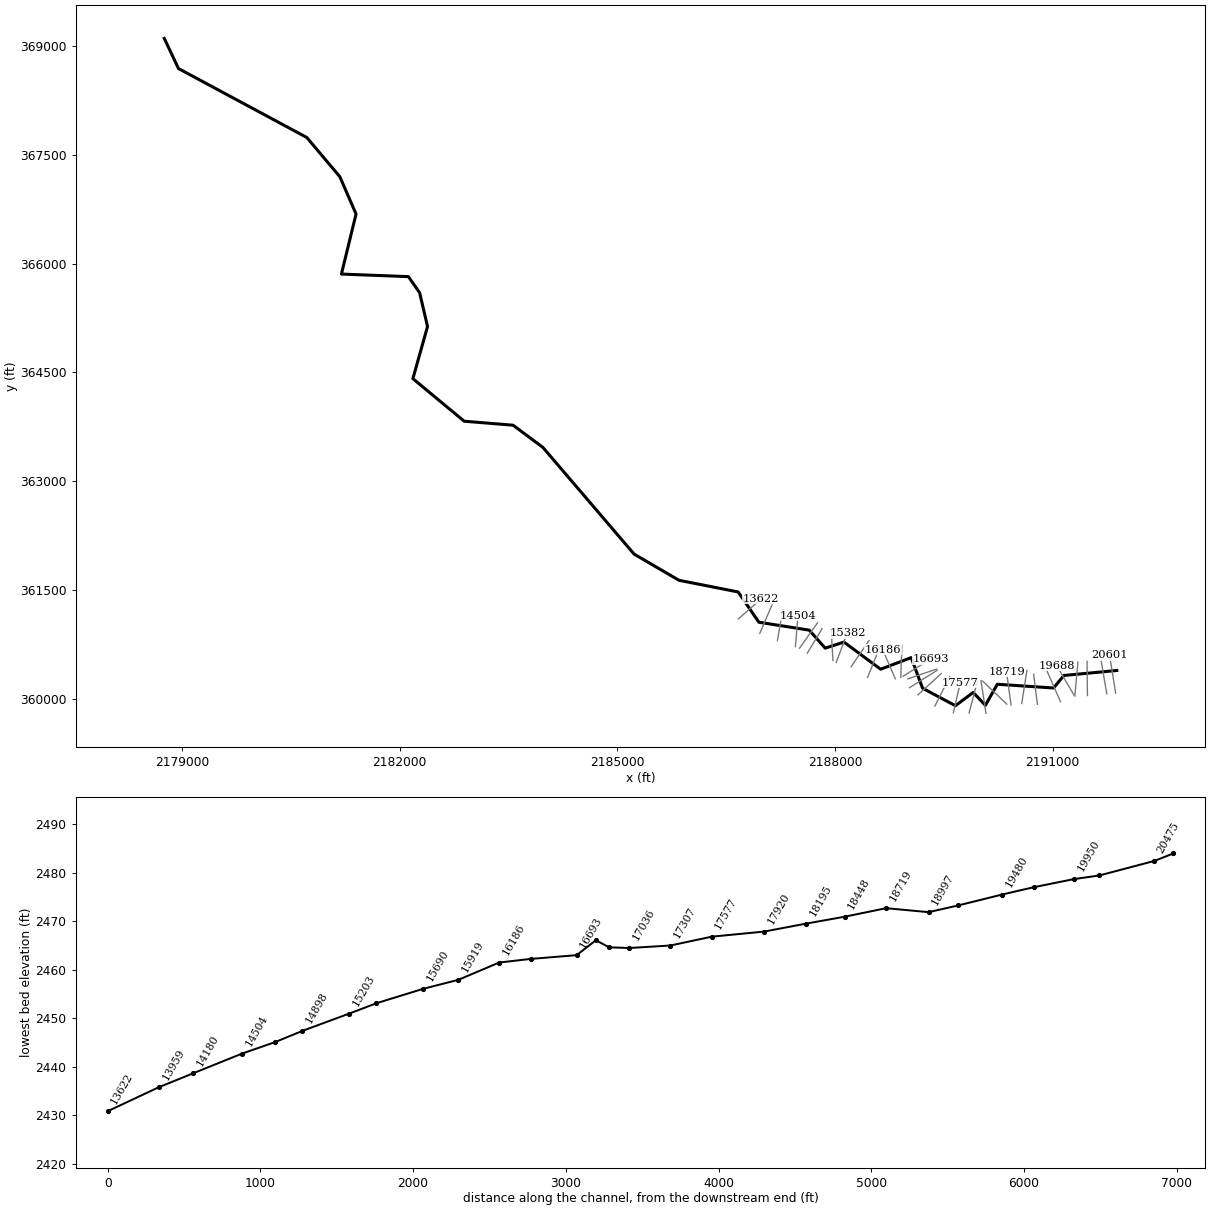
--- SLBCMPRN.prj (project) ---

Proj Title=SLBCMPRN
Current Plan=p01
Default Exp/Contr=0.3,0.1
English Units
Geom File=g02
Flow File=f02
Plan File=p01
BEGIN DESCRIPTION:
Stream Name- Slabcamp Run
Flood Zone: Zone A
Greenbrier County, WV
County-Wide Study
WVDHSEM-2018-3, Flood Risk Project
HEC-RAS Version: 5.0.7
General Notes:
For the Hydrology regression was used.
END DESCRIPTION:
DSS Export Rating Curves= 0
DSS Export Rating Curve Sorted= 0
DSS Export Volume Flow Curves= 0
DXF OffsetX= 0
DXF OffsetY= 0
DXF ScaleX= 0
DXF ScaleY= 0

--- SLBCMPRN.p01 (plan) ---

Plan Title=Floodplain
Program Version=5.07
Short Identifier=Floodplain
Geom File=g02
Flow File=f02
Subcritical Flow
K Sum by GR= 0
Std Step Tol= 0.01
Critical Tol= 0.01
Num of Std Step Trials= 20
Max Error Tol= 0.3
Flow Tol Ratio= 0.001
Split Flow NTrial= 30
Split Flow Tol= 0.02
Split Flow Ratio= 0.02
Log Output Level= 0
Friction Slope Method= 1
Unsteady Friction Slope Method= 2
Unsteady Bridges Friction Slope Method= 1
Parabolic Critical Depth
Global Vel Dist= 0 , 0 , 0
Global Log Level= 0
CheckData=True
Encroach Param=-1 ,0,0, 0
Mapping Interval=1HOUR
Computation Time Step Use Courant=        0
Computation Time Step Use Time Series=    0
Computation Time Step Count To Double=0
Computation Time Step Max Doubling=0
Computation Time Step Max Halving=0
Computation Time Step Residence Courant=0
Run HTab= 0
Run UNet= 0
Run Sediment= 0
Run PostProcess= 0
Run WQNet= 0
Run RASMapper=-1
UNET Theta= 0
UNET Theta Warmup= 0
UNET ZTol= 0
UNET ZSATol= 0
UNET MxIter= 0
UNET Max Iter WO Improvement= 0
UNET MaxInSteps= 0
UNET DtIC= 0
UNET DtMin= 0
UNET MaxCRTS= 0
UNET WFStab= 0
UNET SFStab= 0
UNET WFX= 1
UNET SFX= 1
UNET 1D Methodology=Finite Difference
UNET DSS MLevel= 1
UNET Pardiso=0
UNET DZMax Abort= 0
UNET Use Existing IB Tables= 0
UNET Froude Reduction=False
UNET Froude Limit= 0
UNET Froude Power= 0
UNET D1 Cores= 0
UNET D2 Coriolis=0
UNET D2 Cores= 0
UNET D2 Theta= 1
UNET D2 Theta Warmup= 1
UNET D2 Z Tol= 0.01
UNET D2 Volume Tol= 0.01
UNET D2 Max Iterations= 20
UNET D2 Equation= 0
UNET D2 RampUpFraction=0.1
UNET D2 TimeSlices= 1
UNET D2 BCVolumeCheck=0
UNET D1D2 MaxIter= 0
UNET D1D2 ZTol=0.01
UNET D1D2 QTol=0.1
UNET D1D2 MinQTol=1
Write IC File= 0
Write IC File at Fixed DateTime=0
Write IC File at Sim End=0
Echo Input=False
Echo Parameters=False
Echo Output=False
Write Detailed= 0
HDF Write Warmup=0
HDF Write Time Slices=0
HDF Flush=0
HDF Face Node Velocities=0
HDF Compression= 1
HDF Chunk Size= 1
HDF Spatial Parts= 1
HDF Use Max Rows=0
HDF Fixed Rows= 1
Calibration Method= 0
Calibration Iterations= 20
Calibration Max Change=0.05
Calibration Tolerance=0.2
Calibration Maximum=1.5
Calibration Minimum=0.5
Calibration Optimization Method= 1
WQ AD Non Conservative
WQ ULTIMATE=-1
WQ Max Comp Step=1HOUR
WQ Output Interval=15MIN
WQ Output Selected Increments= 0
WQ Output face flow=0
WQ Output face velocity=0
WQ Output face area=0
WQ Output face dispersion=0
WQ Output cell volume=0
WQ Output cell surface area=0
WQ Output cell continuity=0
WQ Output cumulative cell continuity=0
WQ Output face conc=0
WQ Output face dconc_dx=0
WQ Output face courant=0
WQ Output face peclet=0
WQ Output face adv mass=0
WQ Output face disp mass=0
WQ Output cell mass=0
WQ Output cell source sink temp=0
WQ Output nsm pathways=0
WQ Output nsm derived pathways=0
WQ Output MaxMinRange=-1
WQ Daily Max Min Mean=-1
WQ Daily Range=0
WQ Daily Time=0
WQ Create Restart=0
WQ Fixed Restart=0
WQ System Summary=0
WQ Write To DSS=0
WQ Use Fixed Temperature=0
Sorting and Armoring Iterations= 10
XS Update Threshold= 0.02
Bed Roughness Predictor= 0
Hydraulics Update Threshold= 0.02
Energy Slope Method= 1
Volume Change Method= 1
Sediment Retention Method= 0
XS Weighting Method= 0
Number of US Weighted Cross Sections= 1
Number of DS Weighted Cross Sections= 1
Upstream XS Weight=0
Main XS Weight=1
Downstream XS Weight=0
Number of DS XS's Weighted with US Boundary= 1
Upstream Boundary Weight= 1
Weight of XSs Associated with US Boundary= 0
Number of US XS's Weighted with DS Boundary= 1
Downstream Boundary Weight= 0.5
Weight of XSs Associated with DS Boundary= 0.5
Percentile Method= 0
Sediment Output Level= 3
Mass or Volume Output= 0
Output Increment Type= 1
Profile and TS Output Increment= 1
XS Output Flag= 0
XS Output Increment= 10
Write Gradation File= 0
Read Gradation Hotstart= 0
Write HDF5 File= 1
Write Binary Output= 1
Write DSS Sediment File= 0
SV Curve= 0
Specific Gage Flag= 0

--- SLBCMPRN.f02 (steady flow) ---

Flow Title=Slabcamp Run Flow
Program Version=5.07
Number of Profiles= 6
Profile Names=f1p,f10p,f4p,f2p,f02p,f1pplus
River Rch & RM=Slabcamp Run,Main            ,20601
     619     328     436     524     915     863
River Rch & RM=Slabcamp Run,Main            ,19950
     688     366     486     584    1020     958
River Rch & RM=Slabcamp Run,Main            ,15382
     780     417     552     662    1150    1080
River Rch & RM=Slabcamp Run,Main            ,10451
     970     523     689     825    1430    1340
River Rch & RM=Slabcamp Run,Main            ,9708
    1080     585     769     920    1600    1490
River Rch & RM=Slabcamp Run,Main            ,5188
    1200     654     858    1020    1780    1660
Boundary for River Rch & Prof#=Slabcamp Run,Main            , 1
Up Type= 0
Dn Type= 3
Dn Slope=0.041
Boundary for River Rch & Prof#=Slabcamp Run,Main            , 2
Up Type= 0
Dn Type= 3
Dn Slope=0.041
Boundary for River Rch & Prof#=Slabcamp Run,Main            , 3
Up Type= 0
Dn Type= 3
Dn Slope=0.041
Boundary for River Rch & Prof#=Slabcamp Run,Main            , 4
Up Type= 0
Dn Type= 3
Dn Slope=0.041
Boundary for River Rch & Prof#=Slabcamp Run,Main            , 5
Up Type= 0
Dn Type= 3
Dn Slope=0.041
Boundary for River Rch & Prof#=Slabcamp Run,Main            , 6
Up Type= 0
Dn Type= 3
Dn Slope=0.041
DSS Import GetInterval= 0
DSS Import GetPeak= 0
DSS Import FillOption= 0

--- SLBCMPRN.g02 (geometry) ---

Geom Title=Slabcamp Run
Program Version=5.07

River Reach=Slabcamp Run    ,Main
Reach XY= 30
2191884.97768939360391.3865633162191154.88466139360322.650808394
2191013.05128364360149.8945922262190237.63846439360201.644160643
2190073.61976355359911.5817486492189904.60763438360088.291697055
2189660.21146964359905.7047918892189208.01585389360146.530242363
 2189050.7428723360568.6775473062188629.31983064 360408.91572772
2188123.73553997360782.8769220562187865.75442864360699.211078897
 2187644.9819043360947.5967369822186951.19096905361056.604721054
2186665.42349596361473.6442413032185850.99631906 361634.34470731
 2185231.2682278361995.6714124832183973.68708156363466.991960645
2183563.16809057 363772.142757652182889.47468306363827.124770567
2182182.53744864364413.7420356422182384.41630997 365132.66185765
2182275.50281389365598.1353361462182121.09433006365819.920325637
 2181197.4158957365855.1391618552181399.18632506366682.792943731
2181175.60376698 367197.045524152180720.23492706367737.859075055
2178951.39069572368688.1363739822178755.66339688369104.371433899

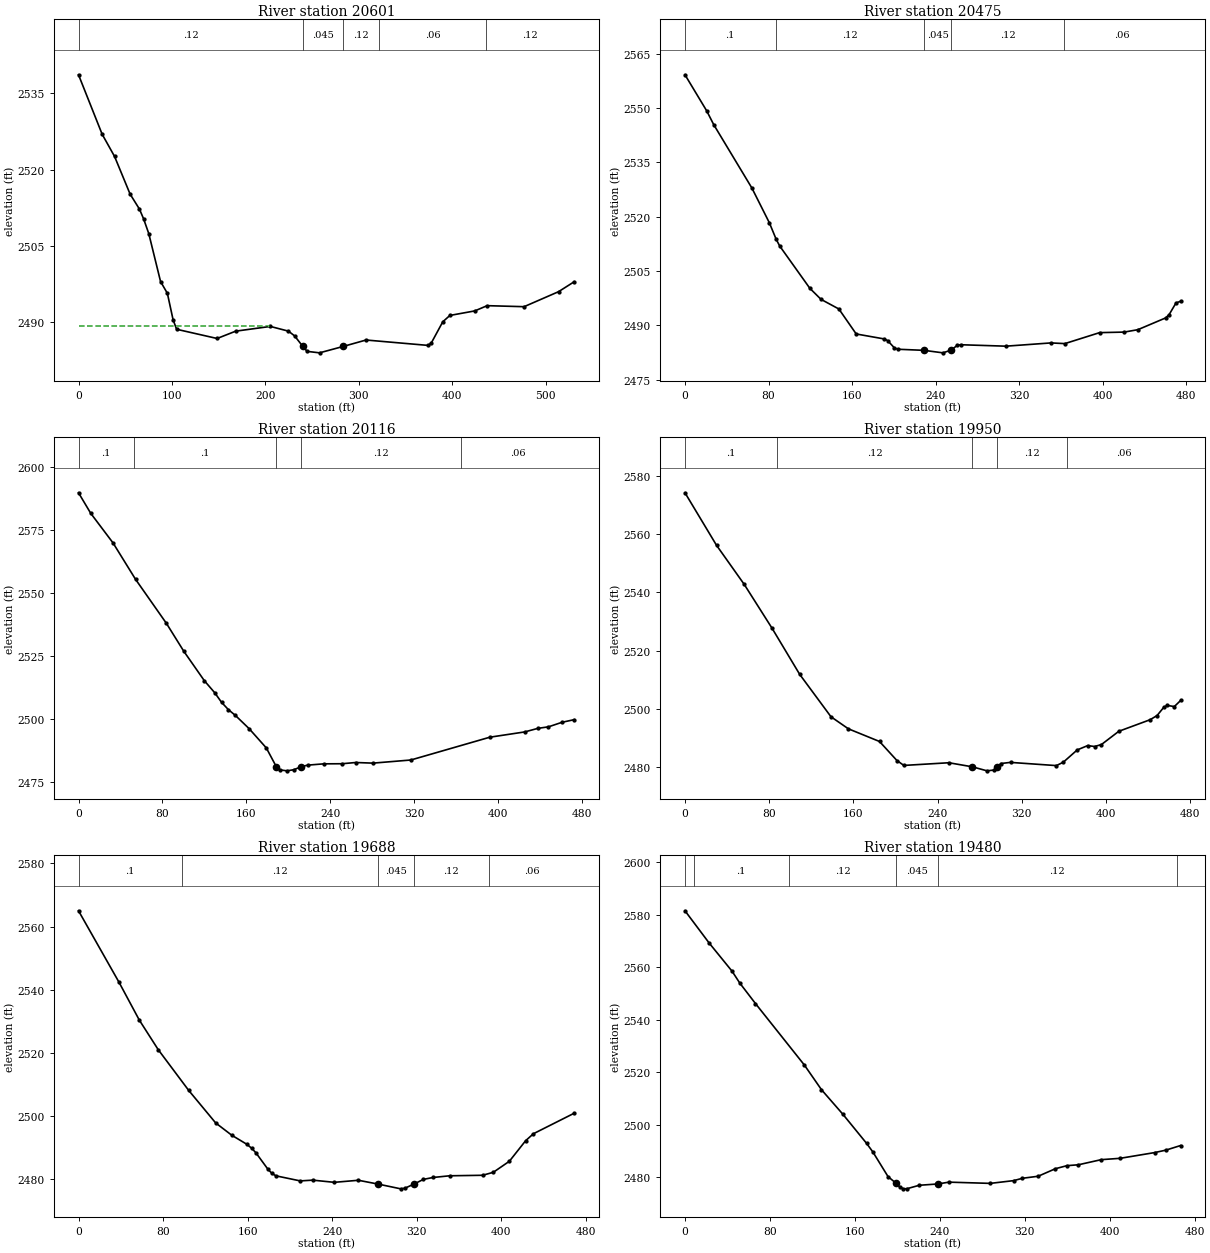
Type RM Length L Ch R = 1 ,20601   ,125,125.7,126.5
XS GIS Cut Line= 2
2191868.68779853360079.297724225 2191785.0014433360603.082106835
#Sta/Elev= 30
       0 2538.63    25.3 2526.94    38.6 2522.57    55.2 2515.18    65.2 2512.23
    69.6 2510.34    75.2 2507.41    87.8 2497.99    95.1 2495.67   101.2 2490.48
     105 2488.61   148.3  2486.8   168.2 2488.24   205.3 2489.17   224.7 2488.24
   231.3  2487.3   239.7 2485.32   244.6 2484.27   257.9 2483.98   283.1 2485.23
   307.7  2486.5   374.2 2485.44   377.5 2485.91   389.8 2490.08   397.4 2491.33
     424 2492.22   437.3 2493.25   476.8 2493.05   513.7    2496   530.4 2497.95
#Mann= 5 ,-1 , 0
       0     .12       0   239.7    .045       0   283.1     .12       0
  321.25     .06       0  436.12     .12       0
#XS Ineff= 2 , 0
          203.74 2489.16
Permanent Ineff=
       F       F
Bank Sta=239.7,283.1
XS Rating Curve= 0 ,0
Exp/Cntr=0.3,0.1

Type RM Length L Ch R = 1 ,20475   ,355,359.3,354.1
XS GIS Cut Line= 5
2191746.77672385  360070.65686132191746.77672385  360070.6568613
2191706.37555742360304.542135744  2191665.974391360538.427410188
  2191665.974391360538.427410188
#Sta/Elev= 30
       0 2559.22    20.8 2549.26    27.5 2545.46    64.1 2527.93    80.8 2518.35
    87.4 2513.74    90.8 2511.89   119.6 2500.24   130.3 2497.19   147.4 2494.53
     164 2487.63   190.4 2486.28     194 2485.82   200.6 2483.78     204 2483.41
   228.9 2483.11     247 2482.42   255.1 2483.19   260.6 2484.47   263.9 2484.66
   307.4 2484.26   350.5 2485.16   363.8 2484.97   397.1    2488   420.6 2488.15
   433.7 2488.81   460.3 2492.06   463.7 2492.99   470.3 2496.22   474.7 2496.66
#Mann= 5 ,-1 , 0
       0      .1       0   86.82     .12       0   228.9    .045       0
   255.1     .12       0  362.97     .06       0
Bank Sta=228.9,255.1
XS Rating Curve= 0 ,0
Exp/Cntr=0.3,0.1

Type RM Length L Ch R = 1 ,20116   ,165.4,166.3,163.5
XS GIS Cut Line= 5
2191479.95328897360046.6472595232191479.95328897360046.647259523
2191477.30562258360282.981492085 2191474.6579562360519.315724647
 2191474.6579562360519.315724647
#Sta/Elev= 30
       0 2589.86    11.7 2581.68    32.9 2569.96    54.4 2555.49    83.9 2537.96
   100.3 2526.99     120 2515.23   129.9 2510.45   136.4 2506.65     143 2503.71
   149.5 2501.48   162.7 2496.19   179.1 2488.53   188.6 2481.11   192.2 2479.81
   198.8 2479.43   205.3 2479.87   211.9 2480.99   218.4 2481.69     234 2482.21
   251.3 2482.25   264.4 2482.74   280.8 2482.49   316.9 2483.73   392.3 2492.79
   425.5 2494.88   438.1  2496.3   448.2 2496.91   461.2 2498.72   472.7 2499.75
#Mann= 5 ,-1 , 0
       0      .1       0   52.85      .1       0   188.6    .045       0
   211.9     .12       0  364.57     .06       0
Bank Sta=188.6,211.9
XS Rating Curve= 0 ,0
Exp/Cntr=0.3,0.1

Type RM Length L Ch R = 1 ,19950   ,239.4,261.4,265
XS GIS Cut Line= 5
2191306.49962399360038.3779623142191306.49962399360038.377962314
2191327.84331459 360272.80740118 2191349.1870052360507.236840046
 2191349.1870052360507.236840046
#Sta/Elev= 30
       0  2574.2      30 2556.14    56.3 2542.72    82.7 2527.67     109  2511.8
   138.7 2497.25   155.2 2493.12   184.8 2488.76   201.3 2482.23   207.9 2480.54
   250.7 2481.46     273 2480.06   286.9 2478.68   293.5 2478.96   296.8 2480.06
   300.1  2481.2   309.2 2481.58   352.8 2480.48   359.4 2481.66   372.6 2485.87
   382.5 2487.35   389.1 2487.04   395.6 2487.72   412.1 2492.27   441.8 2496.24
   448.4 2497.67   454.9 2500.55   458.2 2501.15   464.8 2500.76   470.8 2502.85
#Mann= 5 ,-1 , 0
       0      .1       0   87.17     .12       0     273    .045       0
   296.8     .12       0  363.13     .06       0
Bank Sta=273,296.8
XS Rating Curve= 0 ,0
Exp/Cntr=0.3,0.1

Type RM Length L Ch R = 1 ,19688   ,202.7,208.3,195.2
XS GIS Cut Line= 5
2191295.57177399360051.4937567032191295.57177399360051.493756703
2191176.84705998360253.6010573612191058.12234597360455.708358019
2191058.12234597360455.708358019
#Sta/Elev= 30
       0 2564.99    38.4 2542.32    57.5 2530.41    75.4 2521.05   104.1 2508.21
   129.7 2497.88   144.9 2493.99   159.3  2491.1     164 2489.79   167.8 2488.42
   179.2  2483.2     183 2481.88   186.8 2481.13   209.7 2479.53   221.6 2479.77
   241.9 2479.08   264.7 2479.73   283.6 2478.51   304.8 2477.02   308.6  2477.2
   317.5 2478.56   326.1    2480   335.2 2480.61     351 2481.15   382.2 2481.31
   392.3 2482.25   407.5 2485.74   422.9 2492.25   430.3 2494.46   468.8 2500.94
#Mann= 5 ,-1 , 0
       0      .1       0   97.82     .12       0   283.6    .045       0
   317.5     .12       0  387.88     .06       0
Bank Sta=283.6,317.5
XS Rating Curve= 0 ,0
Exp/Cntr=0.3,0.1

Type RM Length L Ch R = 1 ,19480   ,288.5,287.9,270.7
XS GIS Cut Line= 5
 2191108.4465912359962.010347339 2191108.4465912359962.010347339
2191014.39602666360175.6758744822190920.34546212360389.341401626
2190920.34546212360389.341401626
#Sta/Elev= 30
       0 2581.46    22.8 2569.16    44.4 2558.41    51.6 2553.93    66.4 2546.11
   112.5 2522.66   128.6 2513.27   148.6 2503.99     171 2492.87     177 2489.55
   191.3 2480.15   198.9 2477.61   202.1  2476.3   205.7  2475.5   209.2 2475.56
   220.7 2476.86   237.9 2477.35   248.7 2478.05   287.6 2477.58   309.6 2478.63
   317.8 2479.52   332.7  2480.3     349 2483.18   359.8 2484.33   370.6 2484.67
   392.1 2486.62   409.9 2487.13   442.3 2489.31     453 2490.25   466.9 2492.01
#Mann= 6 ,-1 , 0
       0      .1       0    8.07      .1       0   97.92     .12       0
   198.9    .045       0   237.9     .12       0  463.39     .06       0
Bank Sta=198.9,237.9
XS Rating Curve= 0 ,0
Exp/Cntr=0.3,0.1

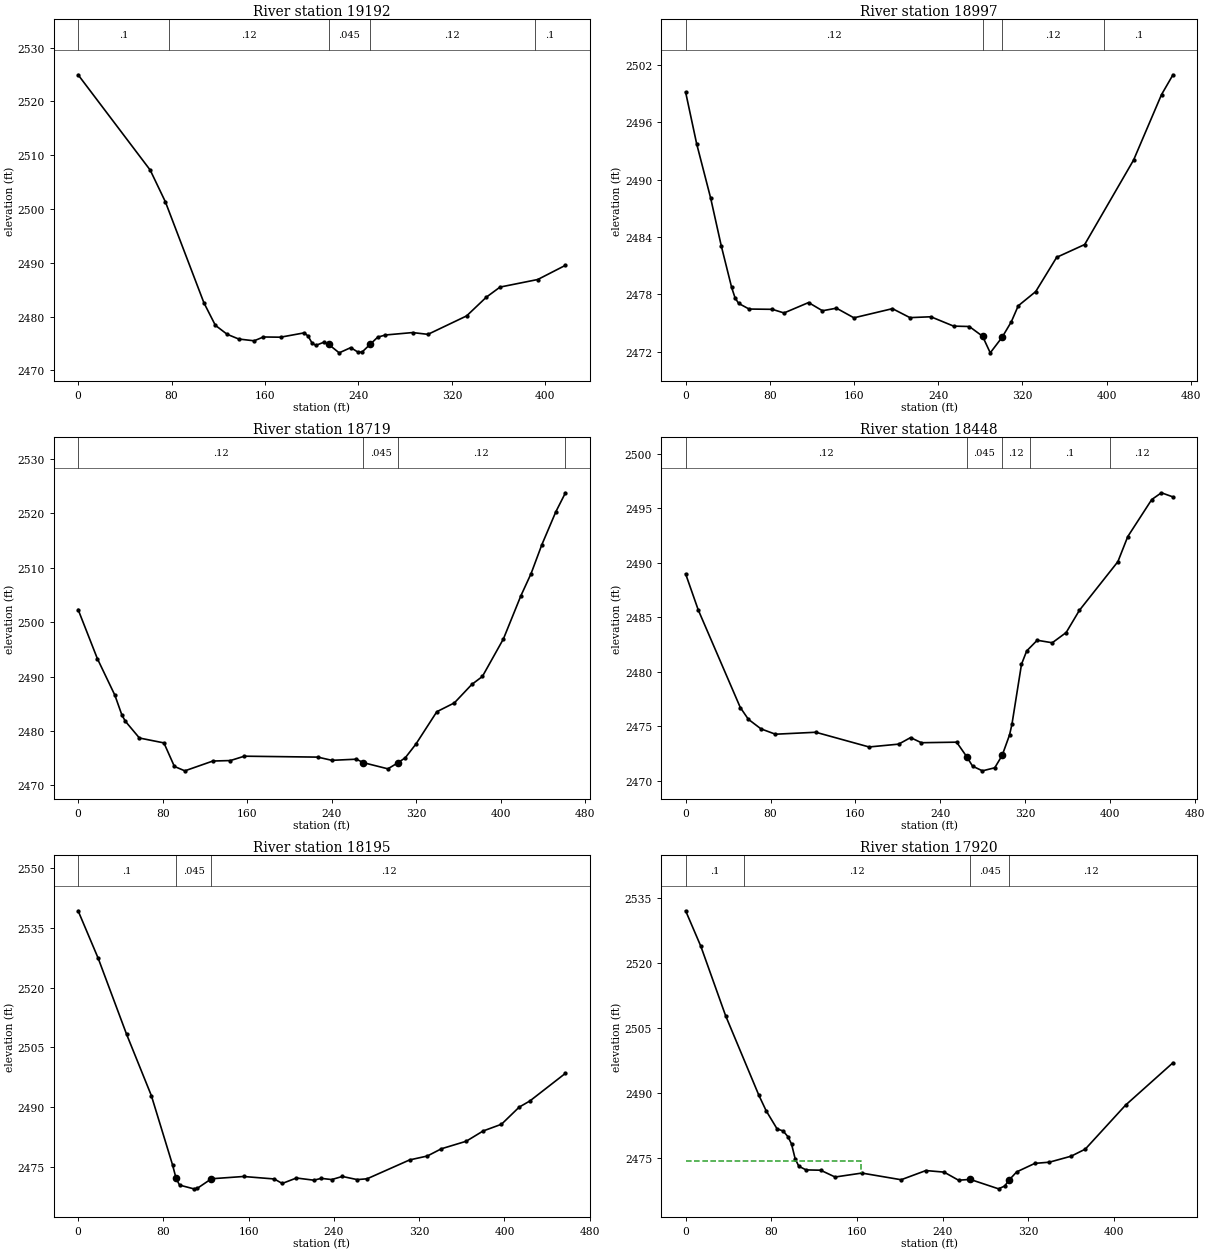
Type RM Length L Ch R = 1 ,19192   ,197.5,194.7,178.3
XS GIS Cut Line= 3
2190790.61159668359925.2541938232190790.61159668359925.254193823
2190738.39342564360339.166951674
#Sta/Elev= 30
       0 2524.97    61.7 2507.25    74.7 2501.35   107.7 2482.56   117.5 2478.37
   127.6  2476.7   137.5 2475.82   150.7 2475.49   158.6  2476.2   173.3 2476.16
   193.7 2476.97     197 2476.33   200.3 2475.06   203.6 2474.64   210.2 2475.21
   214.4 2474.84   223.5 2473.25   233.4 2474.22     240 2473.33   243.3 2473.44
   249.9 2474.81   256.5 2476.17   263.1 2476.57   286.3 2477.02   299.5 2476.69
   332.6 2480.12   349.5 2483.61   361.2 2485.48   393.5 2486.89   417.2 2489.53
#Mann= 5 ,-1 , 0
       0      .1       0   78.13     .12       0   214.4    .045       0
   249.9     .12       0  390.88      .1       0
Bank Sta=214.4,249.9
XS Rating Curve= 0 ,0
Exp/Cntr=0.3,0.1

Type RM Length L Ch R = 1 ,18997   ,269.2,277.8,278.7
XS GIS Cut Line= 5
2190574.34320929359936.4500274072190574.34320929359936.450027407
2190610.04544117360165.1795029422190645.74767305360393.908978477
2190645.74767305360393.908978477
#Sta/Elev= 30
       0 2499.18    10.5 2493.76    23.8 2488.07    33.8  2483.1    43.7 2478.72
      47 2477.61    50.4 2477.04    60.3 2476.45    82.3 2476.42    93.5 2476.04
   116.8 2477.13     130 2476.27   143.3 2476.54   159.9 2475.53   196.5 2476.49
   213.1 2475.55     233 2475.64   254.6 2474.66   269.5 2474.62   282.1  2473.6
   289.4 2471.86   300.6 2473.48   309.4 2475.11     316 2476.79   332.6 2478.28
   352.5 2481.87   379.1 2483.21   425.6 2492.07   452.1 2498.92     463    2501
#Mann= 4 ,-1 , 0
       0     .12       0   282.1    .045       0   300.6     .12       0
  397.88      .1       0
Bank Sta=282.1,300.6
XS Rating Curve= 0 ,0
Exp/Cntr=0.3,0.1

Type RM Length L Ch R = 1 ,18719   ,256.6,271.1,280.1
XS GIS Cut Line= 5
2190426.82902694359915.6321923062190426.82902694359915.632192306
2190395.69818513360144.0698215152190364.56734333360372.507450724
2190364.56734333360372.507450724
#Sta/Elev= 30
       0 2502.31    18.2  2493.3    34.8 2486.57    41.4 2482.95    44.7 2481.79
      58 2478.71    81.2 2477.81    91.1 2473.49     101 2472.68   127.5 2474.48
   144.1 2474.57   157.3 2475.37   226.8  2475.2   240.1 2474.61   263.3 2474.82
   269.9 2474.18   293.1 2473.05   302.7 2474.17   309.6 2475.09   319.6 2477.59
   339.4 2483.54     356 2485.16   372.5 2488.55   382.5 2490.01   402.4 2496.91
   418.9 2504.82   428.6 2508.92   438.8 2514.23     452 2520.26   461.1 2523.75
#Mann= 4 ,-1 , 0
       0     .12       0   269.9    .045       0   302.7     .12       0
  460.35     .06       0
Bank Sta=269.9,302.7
XS Rating Curve= 0 ,0
Exp/Cntr=0.3,0.1

Type RM Length L Ch R = 1 ,18448   ,263.3,253.6,241.7
XS GIS Cut Line= 5
2190367.98990418 359927.621976662190367.98990418 359927.62197666
2190202.27963956360086.4706203962190036.56937495360245.319264132
2190036.56937495360245.319264132
#Sta/Elev= 30
       0 2488.99    11.9 2485.68    51.5 2476.73    59.1 2475.65      71 2474.77
    84.6 2474.28   122.6 2474.46   172.8 2473.11   200.7 2473.37   211.9 2473.97
   222.1  2473.5   255.3 2473.55   264.8 2472.22   270.3 2471.35   279.6 2470.92
   291.2  2471.2   298.2 2472.34   305.1  2474.2   307.4 2475.19   316.4  2480.7
   321.3 2481.92   331.2  2482.9   345.4 2482.67   358.5 2483.61   370.9 2485.64
   407.2 2490.11   416.5 2492.41   439.1 2495.81   448.2 2496.43   459.1 2496.05
#Mann= 5 ,-1 , 0
       0     .12       0   264.8    .045       0   298.2     .12       0
  324.54      .1       0  399.97     .12       0
Bank Sta=264.8,298.2
XS Rating Curve= 0 ,0
Exp/Cntr=0.3,0.1

Type RM Length L Ch R = 1 ,18195   ,268.3,274.6,261.2
XS GIS Cut Line= 5
2190081.18878125359800.1825710662190081.18878125359800.182571066
2190046.76070457360026.1742817852190012.33262789360252.165992505
2190012.33262789360252.165992505
#Sta/Elev= 30
       0 2539.31    18.9 2527.35    45.5 2508.29    68.7 2492.92    88.6 2475.51
    91.9 2472.14    91.9  2472.1    95.2 2470.43   108.5 2469.49     112 2469.65
   125.1 2472.02   155.2 2472.59     184 2471.97   191.5 2470.84   204.8 2472.21
   221.2 2471.66     228 2472.12   237.9 2471.82   247.9  2472.6   261.8 2471.81
   271.1 2472.01     311 2476.75   327.6 2477.73   340.8 2479.55   364.1 2481.44
   379.9 2484.01   397.2 2485.71   413.8 2490.01   423.8 2491.55   457.2  2498.5
#Mann= 3 ,-1 , 0
       0      .1       0    91.9    .045       0   125.1     .12       0
Bank Sta=91.9,125.1
XS Rating Curve= 0 ,0
Exp/Cntr=0.3,0.1

Type RM Length L Ch R = 1 ,17920   ,326.3,342.8,339.4
XS GIS Cut Line= 5
2189848.54671884359805.1848342592189848.54671884359805.184834259
2189906.19499043360025.3620950932189963.84326202360245.539355928
2189963.84326202360245.539355928
#Sta/Elev= 30
       0 2532.04    14.2 2523.85    37.3 2507.85    68.4 2489.46    75.2 2485.88
    85.4  2481.7    91.1  2481.2    95.6 2479.88    98.9 2478.21   102.3  2474.8
   105.7 2473.07   112.5 2472.22   126.1 2472.15   139.6 2470.58   164.6 2471.49
   201.3 2469.95   224.4 2472.07   241.4 2471.71   254.9 2469.84   265.8 2470.03
   292.3 2467.85     298  2468.5   302.4 2469.96   309.2 2471.76   326.2 2473.73
   339.7    2474   360.1 2475.39   373.3 2477.02   410.9 2487.17   455.2 2496.96
#Mann= 4 ,-1 , 0
       0      .1       0   54.47     .12       0   265.8    .045       0
   302.4     .12       0
#XS Ineff= 2 , 0
          163.98 2474.37
Permanent Ineff=
       F       F
Bank Sta=265.8,302.4
XS Rating Curve= 0 ,0
Exp/Cntr=0.3,0.1

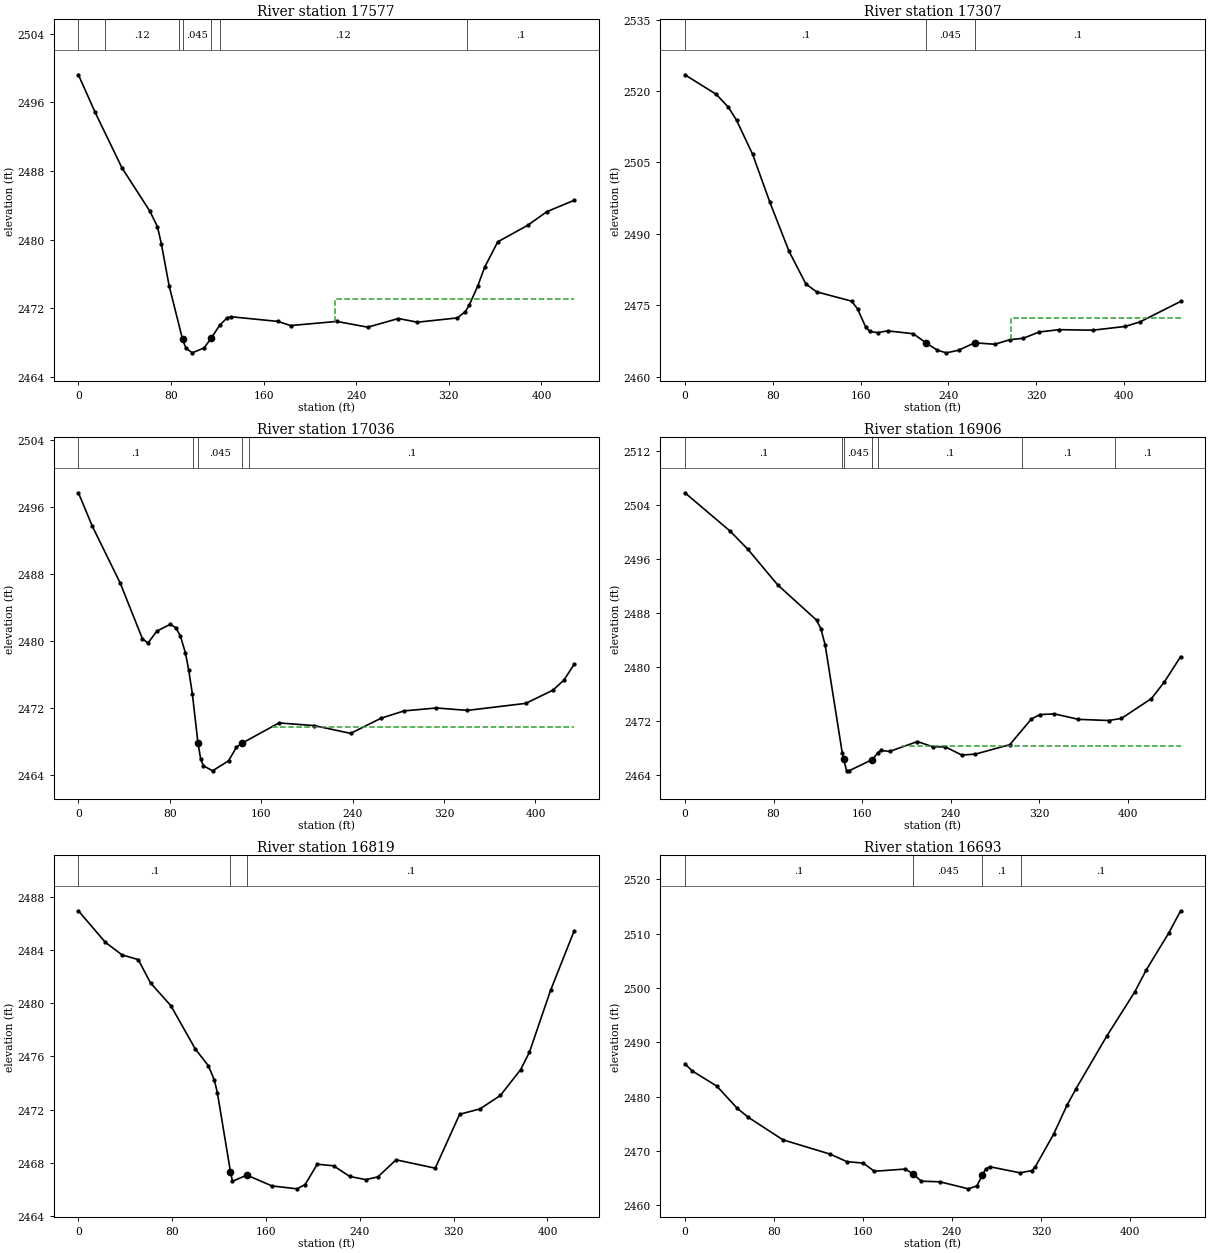
Type RM Length L Ch R = 1 ,17577   ,270.6,270.2,272.7
XS GIS Cut Line= 2
2189632.15106666359808.1251212982189727.77873954360225.520908208
#Sta/Elev= 30
       0  2499.2    14.4 2494.84    37.6 2488.36    61.5 2483.36    68.3  2481.5
    71.6 2479.54    78.4  2474.6      90 2468.36    92.9 2467.34    98.4  2466.8
   108.6 2467.38   114.9 2468.54   122.1 2470.03   128.8 2470.91   132.2    2471
   172.4 2470.46   183.3 2469.98   223.1 2470.46     250 2469.79   276.4  2470.8
   292.9 2470.37   327.4 2470.87   334.2  2471.6   337.5 2472.33   344.9 2474.56
     351  2476.8   362.3 2479.74     388 2481.65   404.8 2483.26   428.2 2484.57
#Mann= 7 ,-1 , 0
       0      .1       0   22.56     .12       0    87.3     .06       0
      90    .045       0   114.9     .06       0   122.1     .12       0
  335.58      .1       0
#XS Ineff= 2 , 0
                          221.37         2473.06
Permanent Ineff=
       F       F
Bank Sta=90,114.9
XS Rating Curve= 0 ,0
Exp/Cntr=0.3,0.1

Type RM Length L Ch R = 1 ,17307   ,266.3,271.5,254.4
XS GIS Cut Line= 5
 2189377.2399195359901.611187919 2189377.2399195359901.611187919
2189479.01114566360103.0626700412189580.78237181360304.514152163
2189580.78237181360304.514152163
#Sta/Elev= 30
       0  2523.4    28.6 2519.28    39.6 2516.58      47 2513.85    61.7 2506.67
    77.4 2496.59    94.8 2486.32   110.2 2479.43     120 2477.79   151.8 2475.84
   157.3 2474.17   164.6  2470.4   168.3 2469.47   175.6 2469.22   184.5  2469.6
   207.9    2469   219.7 2467.05   229.9 2465.53   238.1 2464.98   249.2 2465.53
   263.9 2467.09   282.2 2466.78   295.8 2467.73   308.2 2468.05   322.7 2469.37
     341 2469.85   371.5 2469.74   400.8 2470.52   414.6  2471.5   451.4 2475.78
#Mann= 3 ,-1 , 0
       0      .1       0   219.7    .045       0   263.9      .1       0
#XS Ineff= 2 , 0
                          297.06         2472.36
Permanent Ineff=
       F       F
Bank Sta=219.7,263.9
XS Rating Curve= 0 ,0
Exp/Cntr=0.3,0.1

Type RM Length L Ch R = 1 ,17036   ,127.3,129.5,122
XS GIS Cut Line= 2
2189145.33913537360056.631704126 2189465.0871058360349.736361054
#Sta/Elev= 30
       0 2497.72    12.3 2493.69    36.6 2486.92      56 2480.27    60.9 2479.75
    68.7 2481.18    80.3 2481.98    85.1  2481.6    89.2 2480.61    93.7 2478.55
    96.5 2476.55    99.7 2473.71   104.6 2467.84     107 2465.88   109.4 2465.07
   117.4 2464.46   131.4 2465.66   138.3 2467.28     143 2467.75   175.5 2470.19
   206.5 2469.87   238.2 2468.94   264.8 2470.75     285 2471.63   313.3 2471.98
   340.4 2471.69   391.5 2472.53   415.3 2474.11     425 2475.33   433.8  2477.2
#Mann= 5 ,-1 , 0
       0      .1       0   100.4     .06       0   104.6    .045       0
     143     .06       0     149      .1       0
#XS Ineff= 2 , 0
                          169.45         2469.75
Permanent Ineff=
       F       F
Bank Sta=104.6,143
XS Rating Curve= 0 ,0
Exp/Cntr=0.3,0.1

Type RM Length L Ch R = 1 ,16906   ,90.2,87.3,83.7
XS GIS Cut Line= 5
2189028.57049934360154.8361034442189028.57049934360154.836103444
2189217.89205659360274.0879837412189407.21361384360393.339864038
2189407.21361384360393.339864038
#Sta/Elev= 30
       0 2505.82    40.6 2500.17    56.7 2497.47    83.8 2492.16   118.8 2486.95
   122.7 2485.69   126.6 2483.27     142  2467.3   143.3 2466.33   145.9 2464.65
   148.1 2464.61   169.2 2466.29   174.2 2467.29   176.9 2467.64   184.7 2467.48
   209.9 2468.95   223.7 2468.18   235.1 2468.16   249.9 2466.95   262.2 2467.09
   293.3 2468.49   312.7 2472.28   320.4 2472.95   333.6 2473.05   355.3 2472.24
   382.5 2472.07   394.1 2472.38   421.2 2475.33   432.9  2477.8   447.5 2481.54
#Mann= 7 ,-1 , 0
       0      .1       0     142     .06       0   143.3    .045       0
   169.2     .06       0   174.2      .1       0  303.87      .1       0
  388.16      .1       0
#XS Ineff= 2 , 0
                          195.89         2468.35
Permanent Ineff=
       F       F
Bank Sta=143.3,169.2
XS Rating Curve= 0 ,0
Exp/Cntr=0.3,0.1

Type RM Length L Ch R = 1 ,16819   ,112.7,125.6,138.2
XS GIS Cut Line= 2
2189001.99517364360274.4358577942189401.83011038360411.463687775
#Sta/Elev= 30
       0 2486.94    22.9 2484.58    37.2 2483.63    51.1 2483.27    61.5 2481.52
    78.8 2479.82    99.7 2476.56   110.8 2475.31   115.9 2474.24   118.5 2473.28
   129.7 2467.33   131.4 2466.63   143.72467.088     165 2466.28   186.4 2466.06
   193.3 2466.38   203.7 2467.91   217.6 2467.79   231.4 2466.99   245.1 2466.75
   255.4 2466.96   270.9 2468.24   304.3 2467.61   325.1 2471.66   342.4 2472.06
   359.8 2473.07   377.1 2475.01   384.6 2476.32   402.6 2480.96   422.7 2485.42
#Mann= 3 , 0 , 0
       0      .1       0   129.7    .045       0   143.7      .1       0
Bank Sta=129.7,143.7
XS Rating Curve= 0 ,0
Exp/Cntr(USF)=0,0
Exp/Cntr=0.3,0.1

Type RM Length L Ch R = 1 ,16693   ,258.8,301.7,314.9
XS GIS Cut Line= 5
2188939.82303452360312.1889472722188939.82303452360312.188947272
2189128.30340269360430.9000140322189316.78377087360549.611080791
2189316.78377087360549.611080791
#Sta/Elev= 30
       0 2486.03     6.5 2484.73    28.6 2481.93      47 2477.84    56.9 2476.18
      88 2472.03   130.6 2469.38   145.5    2468   160.2 2467.74   170.2 2466.23
   198.2 2466.64   205.4 2465.65   212.5  2464.4   229.2 2464.29   254.7 2462.99
   262.5 2463.54   267.2  2465.5   270.2 2466.62   274.1 2467.06   301.2 2465.94
   311.7 2466.35   314.8 2467.02   331.5 2473.12   343.3 2478.36   351.6 2481.48
     379  2491.1   404.1 2499.22   414.7 2503.36   434.9 2510.16   445.5 2514.23
#Mann= 4 ,-1 , 0
       0      .1       0   205.4    .045       0   267.2      .1       0
  301.64      .1       0
Bank Sta=205.4,267.2
XS Rating Curve= 0 ,0
Exp/Cntr=0.3,0.1

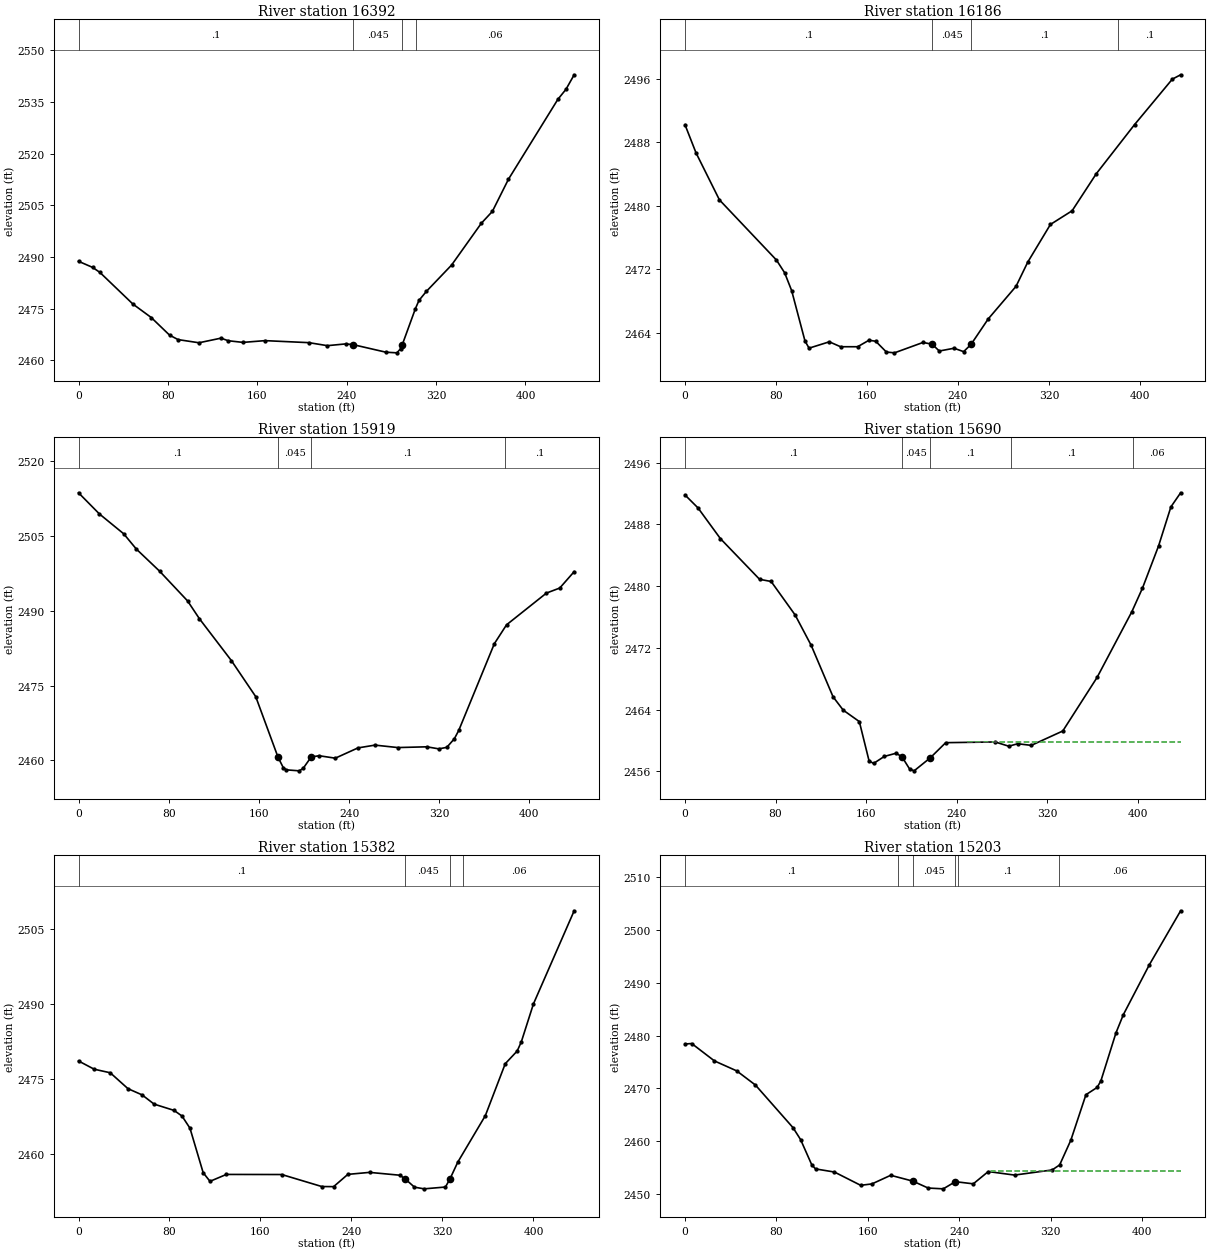
Type RM Length L Ch R = 1 ,16392   ,188.6,205.7,207.4
XS GIS Cut Line= 5
2188907.26196315360295.1604862972188907.26196315360295.160486297
2188914.84472056360516.8299487212188922.42747798360738.499411145
2188922.42747798360738.499411145
#Sta/Elev= 30
       0 2488.76    12.6 2486.99    19.1 2485.55    48.7 2476.35    65.1 2472.45
    81.5 2467.34    89.1 2466.05   107.8 2465.13   127.5 2466.47     134 2465.72
   147.2 2465.24   166.9 2465.75   206.3 2465.16   222.7 2464.29   239.1  2464.8
   245.6  2464.6   275.2 2462.39     285 2462.21   288.3 2463.44   289.7 2464.51
   301.5 2475.01   304.7 2477.41   311.3 2480.02   333.9 2487.67   360.5 2499.78
   370.4 2503.23   384.8 2512.56     429 2535.72   436.3 2538.65   443.6 2542.85
#Mann= 4 ,-1 , 0
       0      .1       0   245.6    .045       0   289.7      .1       0
  302.15     .06       0
Bank Sta=245.6,289.7
XS Rating Curve= 0 ,0
Exp/Cntr=0.3,0.1

Type RM Length L Ch R = 1 ,16186   ,276.4,267,250.7
XS GIS Cut Line= 2
2188831.85381456360276.6193412192188657.94198702360676.168451537
#Sta/Elev= 30
       0 2490.23     9.7 2486.68    30.3 2480.75    80.4 2473.17    87.6 2471.57
    93.8 2469.31   105.5 2462.97   109.1 2462.06   126.9 2462.86   136.8 2462.24
   151.8 2462.24   161.8 2463.06   167.7 2462.93   177.1 2461.57   184.2 2461.47
   209.3 2462.78   217.32462.557   223.6  2461.7   236.6 2462.05     245 2461.62
   251.5 2462.53   266.6 2465.74   291.1 2469.86   301.4 2472.91   321.3 2477.65
   340.4 2479.38   361.6 2484.04   395.3 2490.24   428.5 2495.97   435.8 2496.52
#Mann= 4 ,-1 , 0
       0      .1       0   217.3    .045       0   251.5      .1       0
   380.8      .1       0
Bank Sta=217.3,251.5
XS Rating Curve= 0 ,0
Exp/Cntr=0.3,0.1

Type RM Length L Ch R = 1 ,15919   ,232.9,229,226.3
XS GIS Cut Line= 5
2188449.87019261 360296.796520632188449.87019261 360296.79652063
2188532.13106361360500.6758687412188614.39193461360704.555216853
2188614.39193461360704.555216853
#Sta/Elev= 30
       0 2513.68    18.5 2509.44    40.1 2505.45    51.3 2502.39    71.9 2497.96
    96.7    2492   107.3  2488.4   135.6 2480.02   157.2 2472.79     1772460.628
   181.6 2458.56   184.3  2458.1   195.8  2457.9   199.3  2458.4   206.4 2460.68
   213.4 2460.93   227.8 2460.44   247.9  2462.5     263 2463.06   283.2 2462.57
     309 2462.72   319.6 2462.31   326.7 2462.61   333.4 2464.33   337.3    2466
   368.9 2483.41   379.7 2487.19   415.1 2493.56   426.9 2494.57   439.7 2497.86
#Mann= 4 ,-1 , 0
       0      .1       0     177    .045       0   206.4      .1       0
  378.61      .1       0
#XS Ineff= 2 , 0
                          263.17         2463.03
Permanent Ineff=
       F       F
Bank Sta=177,206.4
XS Rating Curve= 0 ,0
Exp/Cntr=0.3,0.1

Type RM Length L Ch R = 1 ,15690   ,301.8,307.4,310.5
XS GIS Cut Line= 5
2188222.38640591360442.6349822192188222.38640591360442.634982219
2188346.19966021 360623.153964642188470.01291451360803.672947061
2188470.01291451360803.672947061
#Sta/Elev= 30
       0  2491.8    11.5 2490.12    31.3 2486.14    65.9 2480.87    76.1 2480.59
    97.3 2476.25   111.5 2472.31   130.8 2465.65   139.8 2463.92     154 2462.44
   162.6 2457.35   166.6 2457.02   176.1 2457.93   186.5 2458.34   191.7 2457.87
   198.4  2456.3   202.4 2456.06   216.7 2457.75   230.3 2459.71     274  2459.8
     286 2459.25   293.9 2459.57   305.9 2459.36   333.7 2461.22     364 2468.16
   394.7 2476.67   404.1 2479.73   418.3 2485.19   429.2 2490.25   437.8 2492.08
#Mann= 5 ,-1 , 0
       0      .1       0   191.7    .045       0   216.7      .1       0
  287.88      .1       0     396     .06       0
#XS Ineff= 2 , 0
                          249.25         2459.86
Permanent Ineff=
       F       F
Bank Sta=191.7,216.7
XS Rating Curve= 0 ,0
Exp/Cntr=0.3,0.1

Type RM Length L Ch R = 1 ,15382   ,174.3,179.6,190.6
XS GIS Cut Line= 5
2188016.38394125360501.4839380312188016.38394125360501.483938031
 2188093.6158532360705.2368772212188170.84776515360908.989816411
2188170.84776515360908.989816411
#Sta/Elev= 30
       0 2478.63    13.8 2476.98    27.9 2476.27    43.5 2473.09    55.9 2471.85
    66.5    2470      84 2468.75      91 2467.62      98 2465.19   109.6  2456.3
   115.6 2454.57     130 2455.95   178.7 2455.93   213.9 2453.53   224.3 2453.51
   236.8 2455.96   255.9 2456.36   282.6 2455.79   287.5    2455   295.4  2453.4
   303.9 2453.07   322.6 2453.43   326.5    2455   333.5 2458.42   357.7  2467.7
   375.2 2478.08   385.7 2480.62   389.3 2482.43     400 2490.04   435.8 2508.65
#Mann= 4 ,-1 , 0
       0      .1       0   287.5    .045       0   326.5      .1       0
  337.97     .06       0
Bank Sta=287.5,326.5
XS Rating Curve= 0 ,0
Exp/Cntr=0.3,0.1

Type RM Length L Ch R = 1 ,15203   ,307.4,305,289.5
XS GIS Cut Line= 5
2187972.75187059360528.2447422622187972.75187059360528.244742262
2187959.73204133360744.8028398482187946.71221207360961.360937434
2187946.71221207360961.360937434
#Sta/Elev= 30
       0  2478.4     5.9 2478.49    25.8 2475.19    45.3  2473.3    61.7 2470.61
    94.6 2462.52   101.2 2460.27     111 2455.47   114.3  2454.7   130.8 2454.11
   153.8 2451.59   163.6 2451.85   180.1 2453.49   199.5 2452.38   212.9 2451.07
   226.1 2450.92   236.7 2452.28   252.4 2451.87   265.5  2454.2   288.5 2453.53
   321.4  2454.5     328 2455.46   337.8 2460.16     351 2468.78   360.8 2470.16
   364.1 2471.41   377.3 2480.52   383.8 2483.99   406.5 2493.43   433.9 2503.68
#Mann= 6 ,-1 , 0
       0      .1       0   186.7     .06       0   199.5    .045       0
   236.7     .06       0   238.6      .1       0   327.4     .06       0
#XS Ineff= 2 , 0
                          267.95          2454.3
Permanent Ineff=
       F       F
Bank Sta=199.5,236.7
XS Rating Curve= 0 ,0
Exp/Cntr=0.3,0.1

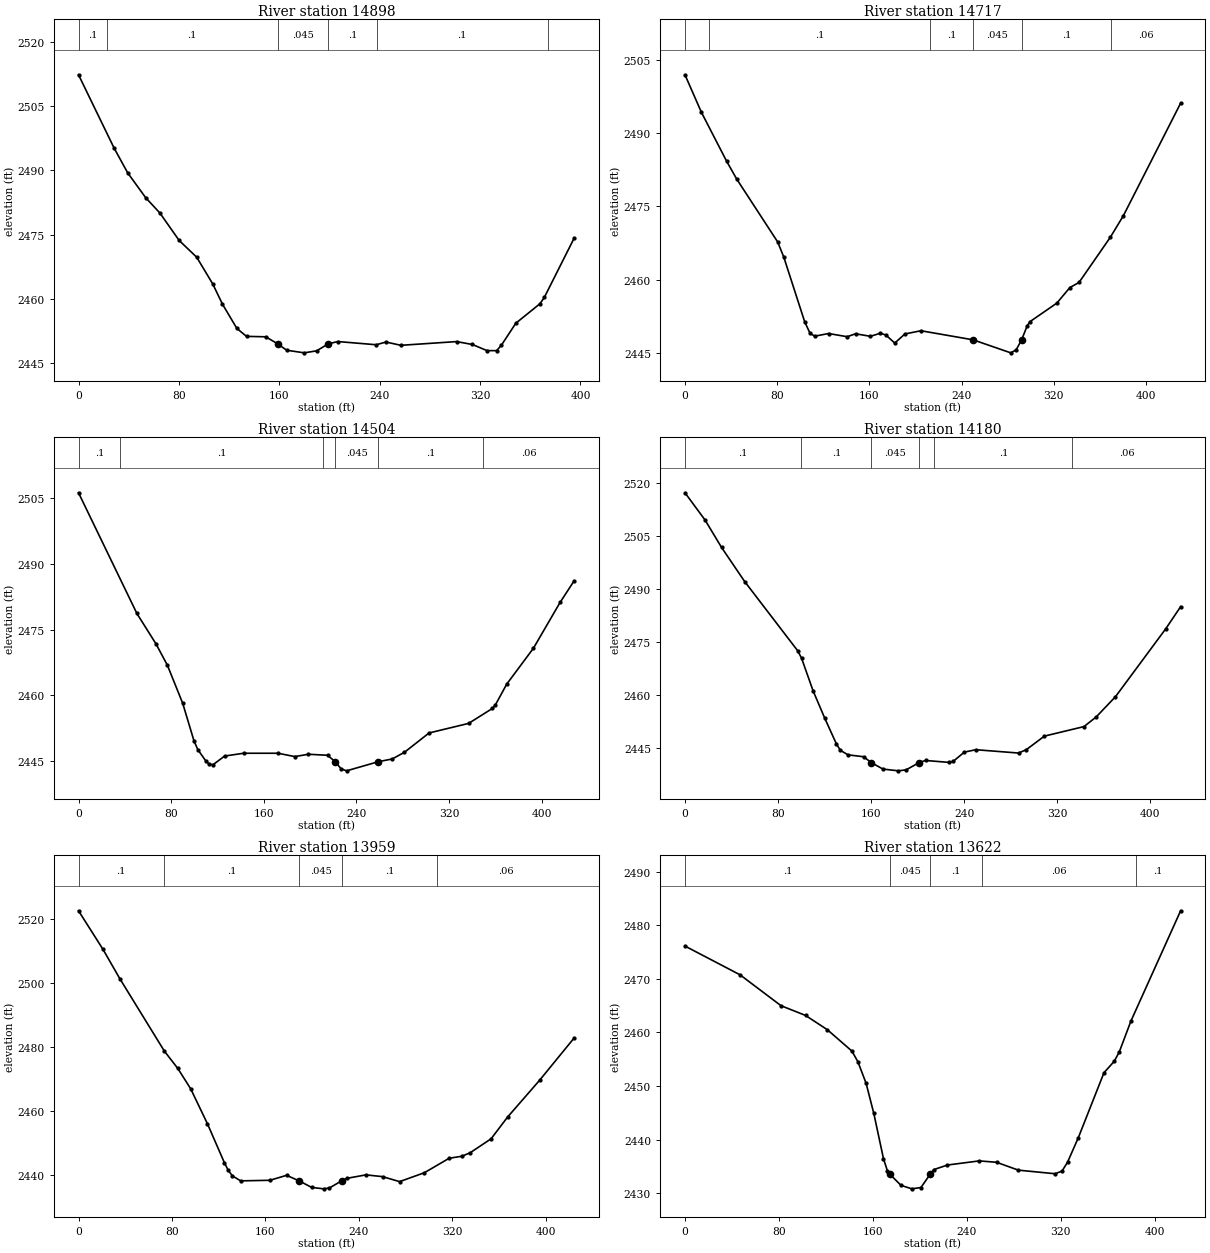
Type RM Length L Ch R = 1 ,14898   ,167.5,181.1,168.1
XS GIS Cut Line= 2
2187618.32582003360629.4798037252187822.48268184360967.580609282
#Sta/Elev= 30
       0 2512.37    28.4 2495.21    39.2 2489.44    53.5 2483.65    64.9 2480.04
    80.2 2473.64    94.2 2469.72     107 2463.46   114.7 2458.76   126.2 2453.07
   133.9 2451.22   149.2 2451.12   158.7 2449.48   165.9 2447.98   179.9 2447.37
   189.8 2447.84     199 2449.47   206.7 2450.01   237.3 2449.26     245  2449.9
   256.9 2449.13   301.3    2450   313.9 2449.32   325.5 2447.89   333.2 2447.88
     337 2449.15   348.5 2454.29   367.7 2458.84   371.2 2460.32     395 2474.19
#Mann= 6 ,-1 , 0
       0      .1       0   22.56      .1       0   158.7    .045       0
     199      .1       0  237.71      .1       0  373.84     .06       0
Bank Sta=158.7,199
XS Rating Curve= 0 ,0
Exp/Cntr=0.3,0.1

Type RM Length L Ch R = 1 ,14717   ,196.1,213,218.2
XS GIS Cut Line= 5
  2187511.212976360698.241945416  2187511.212976360698.241945416
2187635.71883713360873.5214983422187760.22469826361048.801051268
2187760.22469826361048.801051268
#Sta/Elev= 30
       0 2501.91    14.3 2494.21    36.1 2484.24    44.9 2480.57    80.4 2467.72
    85.7 2464.63   103.8 2451.42   108.5 2449.02   112.6 2448.44   124.6 2448.98
   140.7 2448.33     148 2448.93   160.9 2448.41   169.6 2449.05   174.3 2448.67
     182 2447.03   190.8 2448.89   204.7 2449.55     250 2447.69   282.6 2445.03
   287.3 2445.64     292 2447.66   296.7 2450.45   299.1 2451.38   322.6  2455.2
   333.9 2458.38   341.9 2459.44     369 2468.67   380.3 2473.07     430  2496.1
#Mann= 6 ,-1 , 0
       0      .1       0   20.76      .1       0   212.9      .1       0
     250    .045       0     292      .1       0  369.93     .06       0
Bank Sta=250,292
XS Rating Curve= 0 ,0
Exp/Cntr=0.3,0.1

Type RM Length L Ch R = 1 ,14504   ,321,323.8,314.3
XS GIS Cut Line= 5
2187454.68009303360720.0518729942187454.68009303360720.051872994
2187472.59518862360933.3499919232187490.51028422361146.648110851
2187490.51028422361146.648110851
#Sta/Elev= 30
       0 2506.26    50.4 2478.68    66.9 2471.73    76.8 2466.82      90 2458.13
    99.8 2449.49   103.1 2447.53   109.7 2445.06     113 2444.16   116.3 2444.12
   126.2 2446.08   142.6 2446.72   172.3 2446.72   186.8 2445.96   198.6 2446.49
   215.1 2446.26   221.7 2444.79   226.8 2443.16   231.5  2442.7   258.7 2444.77
     271 2445.42   281.5 2446.94   302.8 2451.36   336.9 2453.54   357.4 2456.95
   359.9 2457.69   369.8  2462.5   392.9 2470.72   415.9 2481.18   428.1 2486.15
#Mann= 6 ,-1 , 0
       0      .1       0      36      .1       0   211.5      .1       0
   221.7    .045       0   258.7      .1       0  349.61     .06       0
Bank Sta=221.7,258.7
XS Rating Curve= 0 ,0
Exp/Cntr=0.3,0.1

Type RM Length L Ch R = 1 ,14180   ,227.9,221.4,218.2
XS GIS Cut Line= 5
2187206.47416934360802.8352578492187206.47416934360802.835257849
2187243.41304502361012.6577091142187280.35192069361222.480160379
2187280.35192069361222.480160379
#Sta/Elev= 30
       0 2517.21    17.3 2509.49    31.4 2501.78    51.3 2492.12    96.9 2472.54
   100.2 2470.45   110.2 2461.16   120.2 2453.44   130.2 2446.18   133.6 2444.38
   140.2 2443.11   153.5 2442.58   160.2 2440.91   170.2 2439.09   183.5 2438.59
   190.2 2438.88   201.4 2440.94   206.8 2441.52   227.3 2440.97   230.8 2441.33
   240.2 2443.89   250.1 2444.56   286.8 2443.62   293.5 2444.59     309 2448.41
     343  2451.1   353.4 2453.79   370.1 2459.56   413.4  2478.8   426.1 2485.01
#Mann= 6 ,-1 , 0
       0      .1       0  100.03      .1       0   160.2    .045       0
   201.4      .1       0  214.47      .1       0  333.06     .06       0
Bank Sta=160.2,201.4
XS Rating Curve= 0 ,0
Exp/Cntr=0.3,0.1

Type RM Length L Ch R = 1 ,13959   ,340,336.3,325.2
XS GIS Cut Line= 5
2186963.28672424360901.9455606112186963.28672424360901.945560611
2187047.01522608 361096.818831182187130.74372792361291.692101749
2187130.74372792361291.692101749
#Sta/Elev= 30
       0 2522.56      21 2510.49    35.3  2501.4    73.5 2478.74      85 2473.33
      96 2466.99   110.3 2456.11   124.9 2443.88   128.1 2441.57   131.7  2439.8
   138.8 2438.25   163.8 2438.43   178.1 2439.98   188.8 2438.25   199.5 2436.21
   209.8 2435.76   214.8 2436.04   225.5 2438.32   229.8 2439.05     246 2440.12
   260.2 2439.57   274.8 2438.01     296 2440.79   317.2  2445.3   328.1 2445.94
   335.2 2447.03   353.1 2451.38   367.2 2458.16   394.7 2469.69   424.2 2482.86
#Mann= 5 ,-1 , 0
       0      .1       0   72.87      .1       0   188.8    .045       0
   225.5      .1       0  306.67     .06       0
Bank Sta=188.8,225.5
XS Rating Curve= 0 ,0
Exp/Cntr=0.3,0.1

Type RM Length L Ch R = 1 ,13622   ,234,234.8,232.3
XS GIS Cut Line= 5
2186666.06675109361100.2425588432186666.06675109361100.242558843
2186824.64804345361239.5796704862186983.22933581 361378.91678213
2186983.22933581 361378.91678213
#Sta/Elev= 30
       0 2476.14    46.9 2470.77    81.8    2465   102.7 2463.18   121.3 2460.51
   142.2 2456.52   147.3 2454.53   154.3 2450.49   160.8 2444.92   169.1 2436.41
   172.4 2434.17   174.7 2433.48     184 2431.44   193.3 2430.79     201 2431.04
   208.92433.528   211.9 2434.38   223.6 2435.24   250.7 2436.01   265.4 2435.75
     284 2434.28   315.3 2433.61   321.2 2434.12   325.9 2435.78   335.1 2440.37
   356.9 2452.48   365.7 2454.63     370  2456.4   379.9 2462.15   422.2 2482.73
#Mann= 5 ,-1 , 0
       0      .1       0   174.7    .045       0   208.9      .1       0
  252.63     .06       0  384.17      .1       0
Bank Sta=174.7,208.9
XS Rating Curve= 0 ,0
Exp/Cntr=0.3,0.1