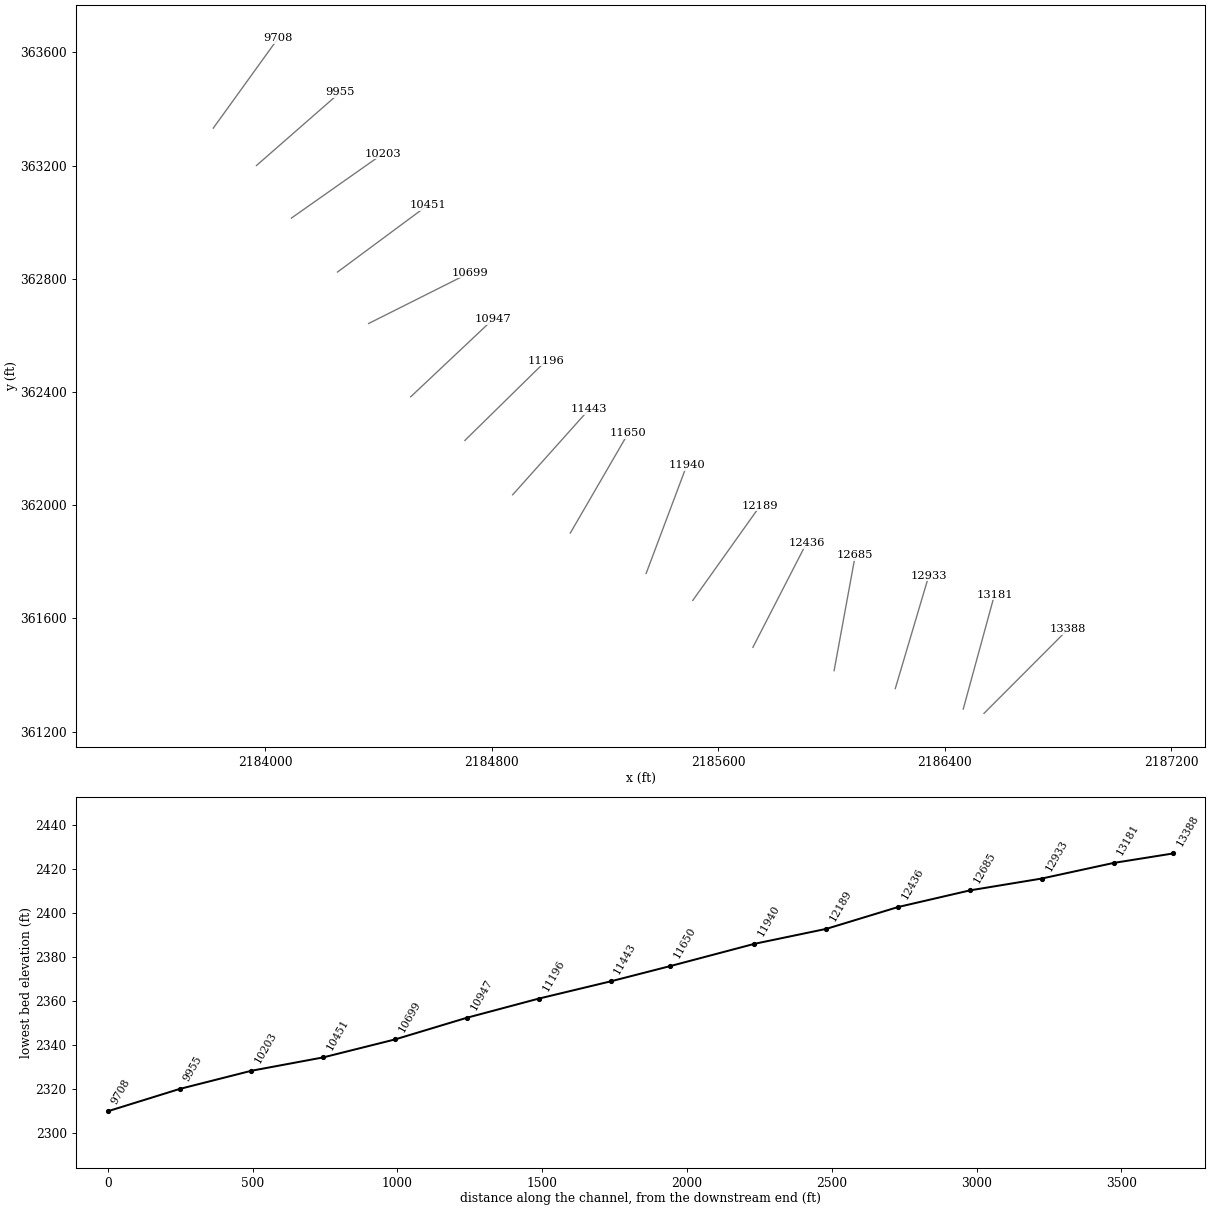
HEC-RAS study SLBCMPRN.prj: SLBCMPRN

--- SLBCMPRN.g02 (geometry) --- (continued)

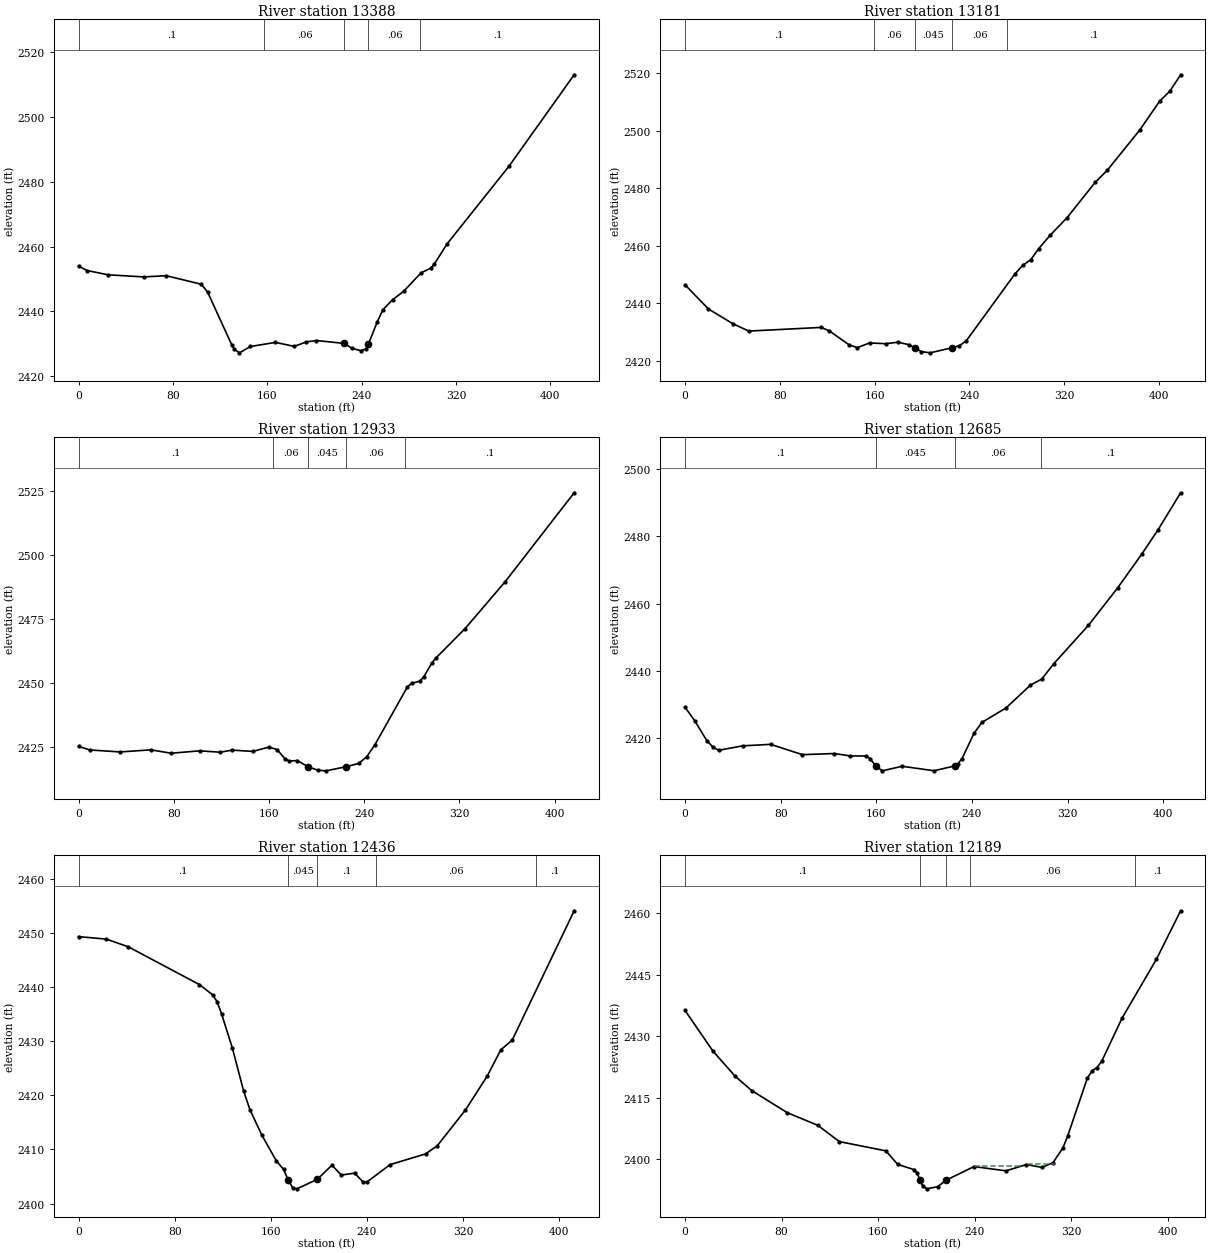
Type RM Length L Ch R = 1 ,13388   ,198.2,206.7,208.2
XS GIS Cut Line= 5
2186538.72447186361264.2040703972186538.72447186361264.204070397
2186687.13361161361412.9904768932186835.54275136 361561.77688339
2186835.54275136 361561.77688339
#Sta/Elev= 30
       0 2453.98     7.2  2452.6    25.3 2451.26    55.7 2450.62    74.3    2451
   104.1 2448.36   109.4 2445.98   129.9 2429.66   132.2 2428.27   136.5 2427.16
   145.8 2429.12     167 2430.39   182.9 2429.15     193 2430.53   201.8 2430.97
   225.5 2430.06     232 2428.54   239.4 2427.84   243.6 2428.32   245.9 2429.91
   253.4 2436.79     258 2440.42   266.3 2443.58   275.6 2446.13   290.5 2451.88
   298.7 2453.33   301.6 2454.52   312.6 2460.86   364.9 2484.76   420.3 2513.08
#Mann= 5 ,-1 , 0
       0      .1       0  157.68     .06       0   225.5    .045       0
   245.9     .06       0  289.99      .1       0
Bank Sta=225.5,245.9
XS Rating Curve= 0 ,0
Exp/Cntr=0.3,0.1

Type RM Length L Ch R = 1 ,13181   ,247.7,248,246.8
XS GIS Cut Line= 5
2186465.39825887361279.4384757262186465.39825887361279.438475726
2186520.53445957361481.2410744662186575.67066028361683.043673206
2186575.67066028361683.043673206
#Sta/Elev= 30
       0 2446.46    19.8 2438.05    40.2 2432.99    53.8 2430.38     115 2431.65
   121.8 2430.45   138.8 2425.52   145.6 2424.64   155.8 2426.26   169.4 2425.99
   179.6 2426.51   188.9 2425.68   193.82424.579   199.6 2423.25   206.9 2422.82
   225.52424.583   231.6  2425.3   237.5 2427.02   278.3 2450.09   285.1  2453.2
   291.9 2455.18   298.7 2459.05   308.5 2463.76   322.5 2469.74   346.3 2482.03
   356.5 2486.23   383.9  2500.2   400.7 2510.22   409.4 2513.73   418.4 2519.38
#Mann= 5 ,-1 , 0
       0      .1       0  159.14     .06       0   193.8    .045       0
   225.5     .06       0  271.86      .1       0
Bank Sta=193.8,225.5
XS Rating Curve= 0 ,0
Exp/Cntr=0.3,0.1

Type RM Length L Ch R = 1 ,12933   ,245.7,248,249.6
XS GIS Cut Line= 5
2186225.45213271361351.8440090552186225.45213271361351.844009055
2186284.65829599361551.4474234862186343.86445927361751.050837917
2186343.86445927361751.050837917
#Sta/Elev= 30
       0 2425.31     9.4 2423.89    34.9 2423.11    60.7 2423.93    77.9 2422.61
   101.8 2423.54   118.9 2423.01   129.2 2423.83   146.3 2423.31     160 2425.01
   166.8 2424.03   173.7 2420.32   177.1 2419.55   183.9 2419.74   192.82417.304
   201.1 2415.96   207.9 2415.72   224.7 2417.32   235.3  2418.6   242.1 2421.22
     249 2425.91   276.3 2448.57   279.8 2449.92   286.6 2450.77     290 2452.43
   296.9 2457.94   300.3 2459.88   324.3 2471.12   358.4 2489.68   416.4 2524.48
#Mann= 5 ,-1 , 0
       0      .1       0  163.22     .06       0   192.8    .045       0
   224.7     .06       0  274.23      .1       0
Bank Sta=192.8,224.7
XS Rating Curve= 0 ,0
Exp/Cntr=0.3,0.1

Type RM Length L Ch R = 1 ,12685   ,252.4,249,244.2
XS GIS Cut Line= 5
2186009.39664771361415.1553220052186009.39664771361415.155322005
2186046.76877311361619.007091648 2186084.1408985361822.858861291
 2186084.1408985361822.858861291
#Sta/Elev= 30
       0 2429.24     8.2 2425.18    18.2 2419.34    23.5 2417.32    28.2 2416.44
    48.2 2417.75    71.6  2418.2    98.2 2415.14     125 2415.47   138.3 2414.75
   151.6 2414.74     155 2413.86   159.62411.768     165 2410.33   181.6 2411.69
   208.3 2410.35   225.42411.774   228.3 2412.44   231.7 2413.97   241.7 2421.46
   248.3 2424.72   268.4 2428.98   288.9 2435.79   298.4 2437.59   308.4 2442.13
   337.3 2453.51   361.8 2464.66   381.8 2474.59   395.6 2481.91   414.5 2492.91
#Mann= 4 ,-1 , 0
       0      .1       0   159.6    .045       0   225.4     .06       0
  297.57      .1       0
Bank Sta=159.6,225.4
XS Rating Curve= 0 ,0
Exp/Cntr=0.3,0.1

Type RM Length L Ch R = 1 ,12436   ,247.6,246.6,243.7
XS GIS Cut Line= 5
2185722.64627491361497.7330039052185722.64627491361497.733003905
 2185816.9267567361681.1721322192185911.20723849361864.611260534
2185911.20723849361864.611260534
#Sta/Elev= 30
       0 2449.35    23.2 2448.89    41.6 2447.45   100.6 2440.49   111.7 2438.58
   115.4  2437.3   119.1 2435.06   128.1  2428.7   137.5 2420.73   142.7 2417.34
   152.4 2412.73   164.6  2407.9   170.7 2406.31   174.3 2404.44   178.1 2402.95
   181.7 2402.72   198.7 2404.47   210.9 2407.09   218.7 2405.27   229.8 2405.62
   237.1 2403.92   240.2 2404.01   259.3  2407.2   288.8 2409.17   298.6  2410.7
     322 2417.29   340.1 2423.55   351.5 2428.44   360.9  2430.2   412.5 2454.13
#Mann= 5 ,-1 , 0
       0      .1       0   174.3    .045       0   198.7      .1       0
  247.18     .06       0   380.6      .1       0
Bank Sta=174.3,198.7
XS Rating Curve= 0 ,0
Exp/Cntr=0.3,0.1

Type RM Length L Ch R = 1 ,12189   ,245.8,248.8,251.7
XS GIS Cut Line= 5
2185510.39831948361663.4892395782185510.39831948361663.489239578
2185629.38603177361830.7904028692185748.37374407 361998.09156616
2185748.37374407 361998.09156616
#Sta/Elev= 30
       0 2436.32    23.2 2426.38    41.7 2420.23    55.4 2416.75    84.8 2411.37
     110 2408.31   127.9 2404.33   166.4 2402.08   176.2 2398.78     190 2397.48
   192.3 2396.66   194.82394.902     197  2393.5   200.3 2392.82   209.3 2393.34
   216.32394.915   239.4 2398.25   265.9 2397.21   282.9 2398.75   295.8 2398.04
     305 2399.24   313.1 2402.81   316.9 2405.59   333.2 2419.72   337.2 2421.57
   341.3 2422.38   345.2  2423.9   362.1 2434.45   390.5 2448.76   410.6  2460.6
#Mann= 5 ,-1 , 0
       0      .1       0   194.8    .045       0   216.3      .1       0
  236.49     .06       0  372.97      .1       0
#XS Ineff= 2 ,-1
  240.38  278.22 2398.32  284.23  307.65 2398.79
Permanent Ineff=
       F       F
Bank Sta=194.8,216.3
XS Rating Curve= 0 ,0
Exp/Cntr=0.3,0.1

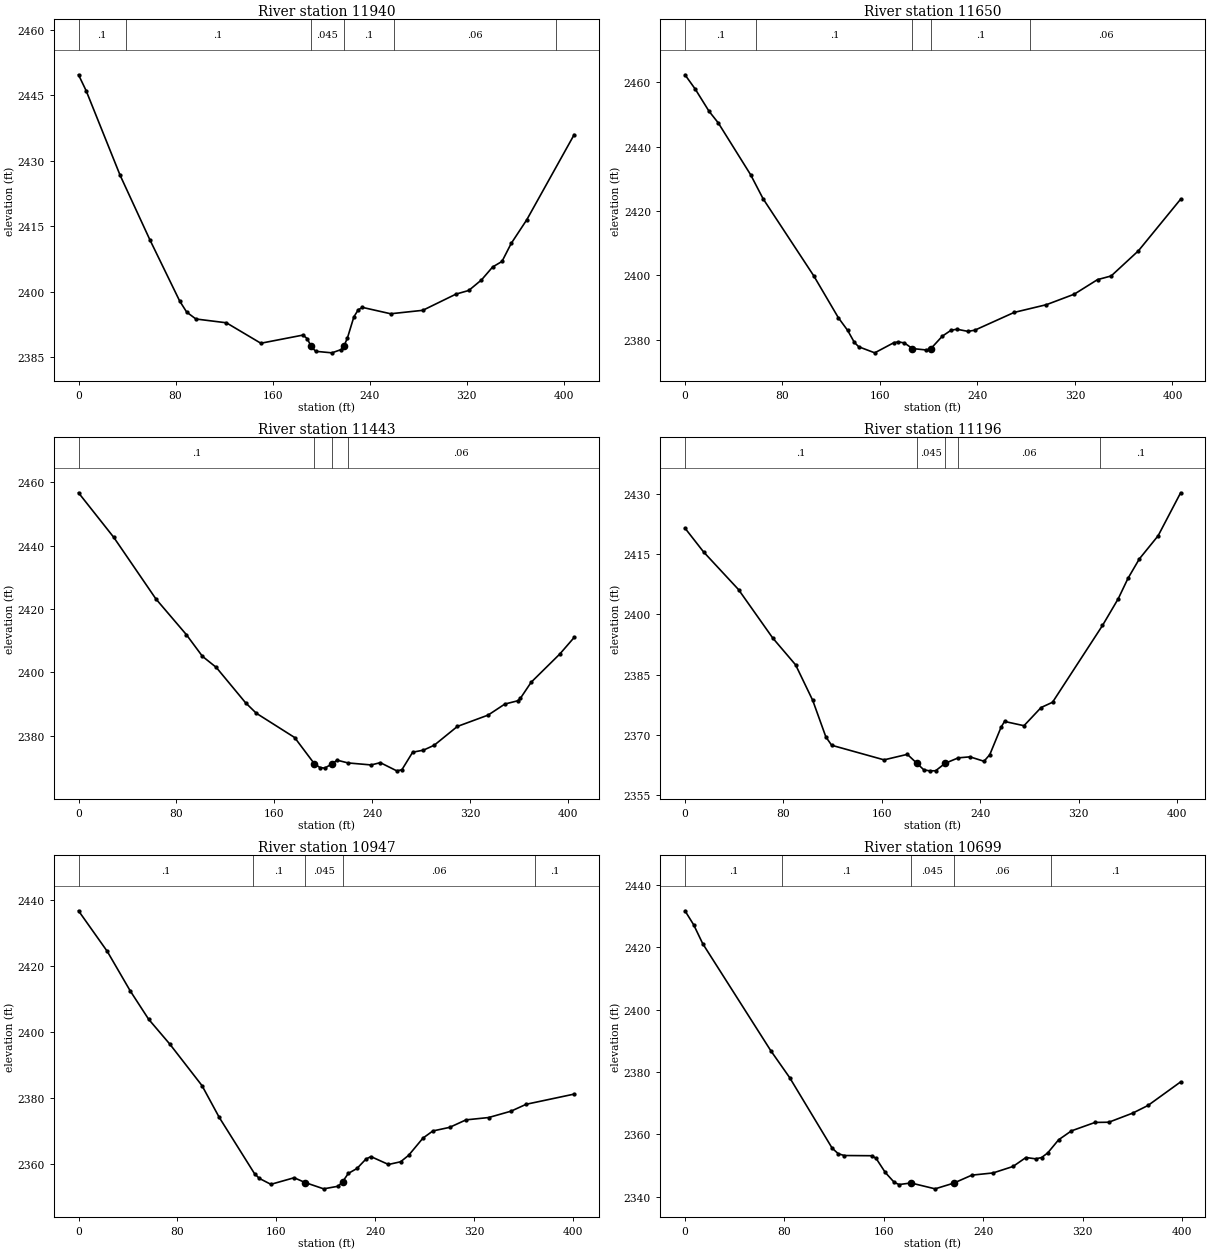
Type RM Length L Ch R = 1 ,11940   ,290.8,289.9,287.3
XS GIS Cut Line= 5
2185345.58572502361758.5396346292185345.58572502361758.539634629
2185417.37743767361949.8093608622185489.16915032362141.079087096
2185489.16915032362141.079087096
#Sta/Elev= 30
       0 2449.75     6.3 2446.09    34.3  2426.7    58.8 2411.93    83.4 2397.87
    89.2 2395.32    96.8 2393.75   121.9 2392.88   150.3 2388.19     185 2390.06
   188.6 2389.24   191.6 2387.54   195.5 2386.34   208.9 2385.99   216.5 2386.74
   218.82387.526   221.7 2389.41     227 2394.24   230.6 2395.86   234.1 2396.41
   257.3 2394.95   283.8 2395.74   311.2 2399.46   321.7 2400.29   332.2 2402.71
   341.4 2405.68   349.1 2406.95   356.7 2411.08   369.5 2416.49   408.6 2436.02
#Mann= 6 ,-1 , 0
       0      .1       0   38.77      .1       0   191.6    .045       0
   218.8      .1       0  260.06     .06       0  393.75      .1       0
Bank Sta=191.6,218.8
XS Rating Curve= 0 ,0
Exp/Cntr=0.3,0.1

Type RM Length L Ch R = 1 ,11650   ,208.9,207.1,205
XS GIS Cut Line= 5
2185077.87666202361901.5314148152185077.87666202361901.531414815
2185179.88540969 362077.443638392185281.89415736362253.355861965
2185281.89415736362253.355861965
#Sta/Elev= 30
       0 2462.37     8.4 2457.93    19.7 2451.05    27.3 2447.41    53.9 2431.26
    64.1 2423.81   105.7 2399.82   125.9 2386.78   133.5 2382.86     139 2379.12
   142.6 2377.77   155.7 2375.89   171.4 2379.05   175.2 2379.31   180.1 2378.95
   186.6 2377.22     198 2376.78   201.8 2377.21   211.2 2381.09   218.5 2382.96
   223.3 2383.22   232.1 2382.57   237.7 2382.92   270.1 2388.46   296.6 2390.87
   319.4 2394.13   338.5 2398.66   349.7  2399.8   372.1 2407.64   406.7 2423.68
#Mann= 5 ,-1 , 0
       0      .1       0   58.48      .1       0   186.6    .045       0
   201.8      .1       0  283.48     .06       0
Bank Sta=186.6,201.8
XS Rating Curve= 0 ,0
Exp/Cntr=0.3,0.1

Type RM Length L Ch R = 1 ,11443   ,247.6,247.8,247.4
XS GIS Cut Line= 5
2184874.33987313362036.7059810652184874.33987313362036.705981065
2185009.22648906362187.6067148932185144.11310499362338.507448721
2185144.11310499362338.507448721
#Sta/Elev= 30
       0 2456.65    28.8 2442.58    63.2 2423.15      88 2411.92   101.2 2405.04
   112.5 2401.54   136.4 2390.39   145.2 2387.07   176.5 2379.41   192.5 2371.18
   197.2 2369.92   201.1 2369.75   206.8 2371.04   211.2 2372.26     220 2371.39
     239 2370.75   246.5 2371.47   259.9 2368.89   264.1 2369.23   272.9 2374.77
   281.7 2375.42   290.5 2376.97   309.4  2382.9   334.5 2386.48   348.2 2389.97
   358.6 2390.99   360.9 2391.79   369.7 2396.86   393.1 2405.77   404.8 2410.99
#Mann= 4 ,-1 , 0
       0      .1       0   192.5    .045       0   206.8      .1       0
     220     .06       0
Bank Sta=192.5,206.8
XS Rating Curve= 0 ,0
Exp/Cntr=0.3,0.1

Type RM Length L Ch R = 1 ,11196   ,249.3,248.3,247.4
XS GIS Cut Line= 5
2184705.58180619362228.7629595332184705.58180619362228.762959533
2184849.25422524362369.9007286322184992.92664429 362511.03849773
2184992.92664429 362511.03849773
#Sta/Elev= 30
       0 2421.39    15.1 2415.48    43.5 2406.12    71.3 2394.08    89.9  2387.4
   103.8 2378.58   114.5 2369.48   119.2 2367.41   161.8 2363.78   180.7 2365.15
   188.5 2362.92   194.1  2361.3   198.8 2361.05   203.7 2361.07   211.42362.921
   222.1 2364.28   231.6 2364.53     243 2363.43   247.7 2365.07   256.9 2371.91
   259.7 2373.33   275.5 2372.27   289.4 2376.79   298.7  2378.1   339.3 2397.19
   352.1 2403.84     360  2408.9   369.2 2413.72   384.5 2419.49   402.8 2430.18
#Mann= 5 ,-1 , 0
       0      .1       0   188.5    .045       0   211.4      .1       0
   222.1     .06       0  337.41      .1       0
Bank Sta=188.5,211.4
XS Rating Curve= 0 ,0
Exp/Cntr=0.3,0.1

Type RM Length L Ch R = 1 ,10947   ,251.8,248.2,243.9
XS GIS Cut Line= 5
2184514.31901664362383.0172268322184514.31901664362383.017226832
2184660.19270965 362520.497212042184806.06640265362657.977197247
2184806.06640265362657.977197247
#Sta/Elev= 30
       0  2436.8    23.3 2424.44    41.8 2412.48    56.7 2403.86    73.9 2396.27
    99.9 2383.68   113.8 2374.05   142.4 2356.92   146.3 2355.49   155.6  2353.7
   174.4  2355.7   183.4 2354.23   198.3 2352.33     210 2353.12   213.6 2354.48
   218.2 2357.01   225.2 2358.51   232.5 2361.38   236.5 2362.13   250.7 2359.73
   260.5 2360.55     267 2362.51   278.6 2367.74   286.6 2369.91   300.2 2371.01
   313.4 2373.28   331.7 2373.99   349.8 2375.92   362.1 2378.02   400.9 2381.11
#Mann= 5 ,-1 , 0
       0      .1       0  141.28      .1       0   183.4    .045       0
   213.6     .06       0  369.14      .1       0
Bank Sta=183.4,213.6
XS Rating Curve= 0 ,0
Exp/Cntr=0.3,0.1

Type RM Length L Ch R = 1 ,10699   ,244.3,247.7,249.4
XS GIS Cut Line= 5
2184365.61675463362641.9488882382184365.61675463362641.948888238
2184543.86713132362731.4295400552184722.11750801362820.910191873
2184722.11750801362820.910191873
#Sta/Elev= 30
       0 2431.74       7 2427.24    14.3 2421.16    69.1 2386.79    84.2  2378.2
   118.4 2355.55   123.3 2353.75   128.1 2353.16   150.2 2353.09   153.8 2352.25
   161.2 2347.72   168.5 2344.51   172.3 2343.84   181.9 2344.34   201.3 2342.46
   216.2 2344.28   230.9 2346.86   247.9 2347.56     264 2349.64   274.4 2352.52
   282.3 2352.09     287 2352.51   291.9 2353.98   300.7 2358.21     311 2361.07
     330 2363.78   341.1 2363.85   360.3 2366.77   372.6 2369.22   398.9  2376.8
#Mann= 5 ,-1 , 0
       0      .1       0   77.85      .1       0   181.9    .045       0
   216.2     .06       0  294.45      .1       0
Bank Sta=181.9,216.2
XS Rating Curve= 0 ,0
Exp/Cntr=0.3,0.1

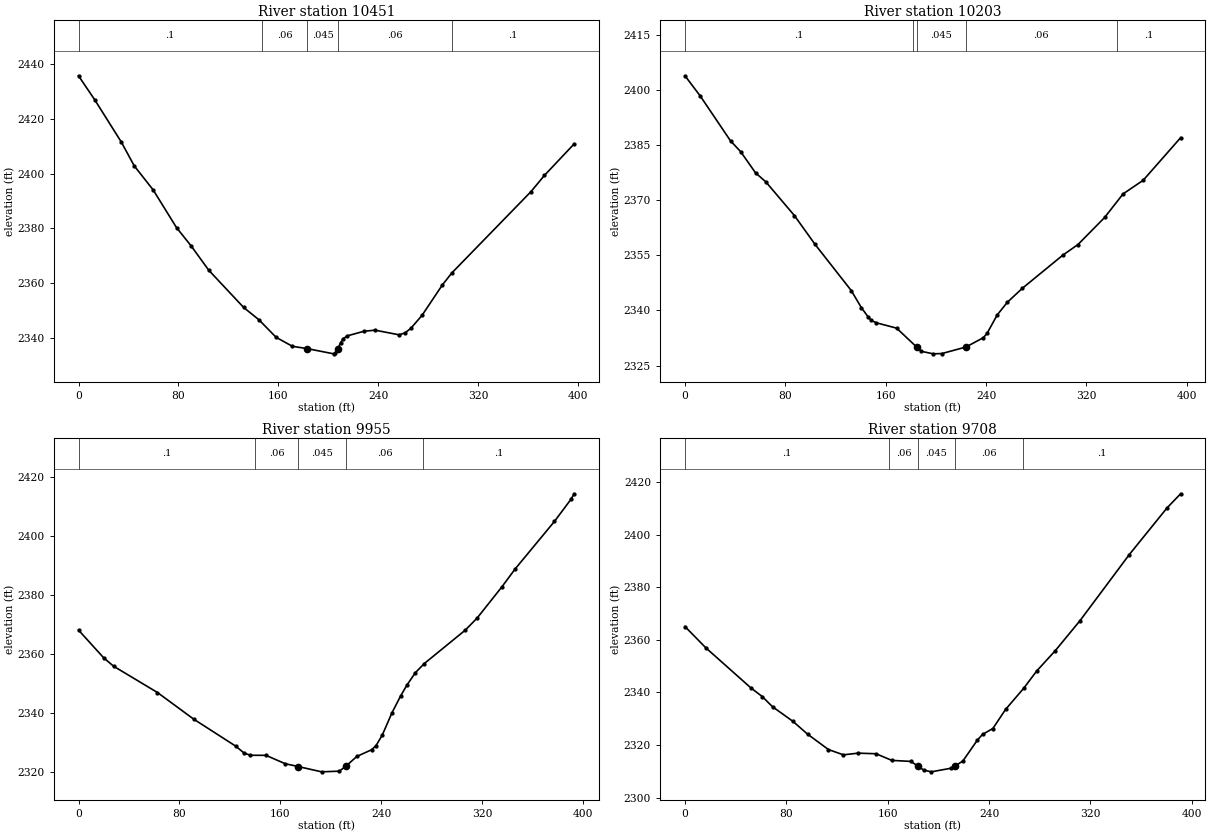
Type RM Length L Ch R = 1 ,10451   ,247.7,248.2,246.6
XS GIS Cut Line= 5
 2184255.7657266362823.818878867 2184255.7657266362823.818878867
2184415.24612179362942.0049149412184574.72651699363060.190951016
2184574.72651699363060.190951016
#Sta/Elev= 30
       0 2435.62    12.9 2426.93    34.3 2411.46    44.6 2402.82    59.8 2394.02
    78.5 2380.29    90.3 2373.57   104.3 2364.77   132.3 2351.18   144.5  2346.7
   158.3  2340.3   171.3 2337.04   183.22336.189   204.4 2334.29   205.8 2334.52
   207.82336.164   209.9 2338.34   212.2 2339.85   215.4 2340.86   228.6 2342.51
   237.5 2342.92   256.8 2341.22   261.5 2341.93   266.2 2343.59   275.2 2348.34
   291.5 2359.44     299 2363.76   362.3 2393.35   373.2 2399.32     397  2410.8
#Mann= 5 ,-1 , 0
       0      .1       0  146.97     .06       0   183.2    .045       0
   207.8     .06       0  299.48      .1       0
Bank Sta=183.2,207.8
XS Rating Curve= 0 ,0
Exp/Cntr=0.3,0.1

Type RM Length L Ch R = 1 ,10203   ,245.3,248.1,249
XS GIS Cut Line= 5
2184092.85360598363014.4081795242184092.85360598363014.408179524
2184254.39062261363128.1248649342184415.92763924363241.841550343
2184415.92763924363241.841550343
#Sta/Elev= 30
       0 2403.84    12.2 2398.33    36.3 2386.14    44.3 2383.23    56.3 2377.41
    64.4    2375    87.2 2365.83   103.7 2357.97   132.6 2345.39   140.6 2340.76
   146.1 2338.21   148.6 2337.27   152.6 2336.64   168.7 2335.19   184.7 2330.04
   188.5 2328.88   197.9  2328.2   204.8 2328.28   223.92330.049   237.9  2332.6
   240.9 2333.83   248.9 2338.79     257 2342.24     269 2346.05   301.1 2355.02
   313.3 2357.94   334.5 2365.29   349.2  2371.7   365.3 2375.43   395.1    2387
#Mann= 5 ,-1 , 0
       0      .1       0   181.9     .06       0   184.7    .045       0
   223.9     .06       0  344.15      .1       0
Bank Sta=184.7,223.9
XS Rating Curve= 0 ,0
Exp/Cntr=0.3,0.1

Type RM Length L Ch R = 1 ,9955    ,243.8,247.6,251
XS GIS Cut Line= 5
2183969.64822034363200.3081889272183969.64822034363200.308188927
2184117.58391817 363329.71693952  2184265.519616363459.125690113
  2184265.519616363459.125690113
#Sta/Elev= 30
       0 2367.96      20 2358.54    27.8 2355.72    62.6  2346.8    91.4 2337.76
   124.7 2328.61   131.2 2326.32   136.2 2325.53   148.7  2325.5   163.9 2322.67
   174.2 2321.71   192.8 2319.91   206.8 2320.14   211.8 2321.73   220.7 2325.12
   232.4 2327.39   235.9 2328.76   240.9 2332.36   248.6 2339.92   255.4 2345.58
   260.3 2349.21   267.2 2353.54   274.2  2356.6   306.8 2367.96   316.1 2372.02
   335.6 2382.51   346.3 2388.69   377.5 2404.81   390.6 2412.31   393.1 2414.16
#Mann= 5 ,-1 , 0
       0      .1       0  139.97     .06       0   174.2    .045       0
   211.8     .06       0  273.55      .1       0
Bank Sta=174.2,211.8
XS Rating Curve= 0 ,0
Exp/Cntr=0.3,0.1

Type RM Length L Ch R = 1 ,9708    ,247.5,248.5,248.3
XS GIS Cut Line= 5
 2183817.0562053363332.414975397 2183817.0562053363332.414975397
2183931.46259188363491.0662779142184045.86897847363649.717580432
2184045.86897847363649.717580432
#Sta/Elev= 30
       0 2365.04    16.5 2356.93    52.1 2341.67      61 2338.41    69.1 2334.53
    85.2 2328.98    96.8 2324.09   113.2 2318.26     125 2316.24   136.7 2316.88
   150.8 2316.65   163.3 2314.12   178.3 2313.74   184.12311.848   188.4 2310.45
   194.4 2309.77   209.6 2311.11   212.82311.847   219.4 2313.93   230.7  2321.8
   234.9 2324.03     243 2326.25     253  2333.5   267.3 2341.53   277.7 2348.19
   292.3 2355.88   311.8  2367.3   350.6 2392.37   380.5 2410.19   391.2 2415.55
#Mann= 5 ,-1 , 0
       0      .1       0  160.92     .06       0   184.1    .045       0
   212.8     .06       0  266.79      .1       0
Bank Sta=184.1,212.8
XS Rating Curve= 0 ,0
Exp/Cntr=0.3,0.1