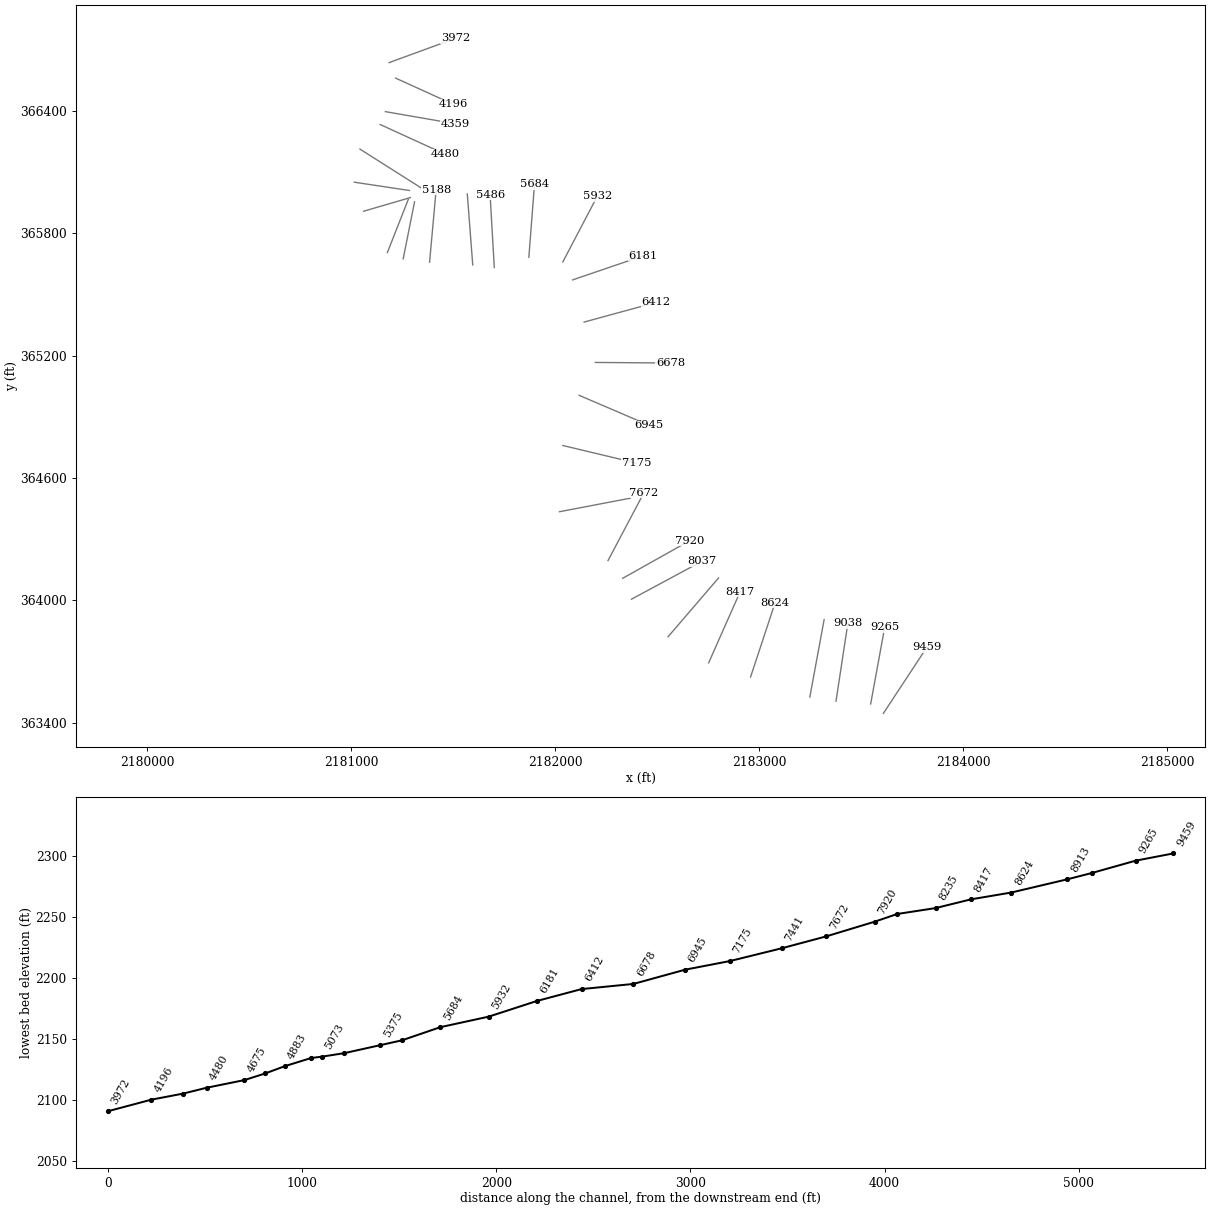
HEC-RAS study SLBCMPRN.prj: SLBCMPRN

--- SLBCMPRN.g02 (geometry) --- (continued)

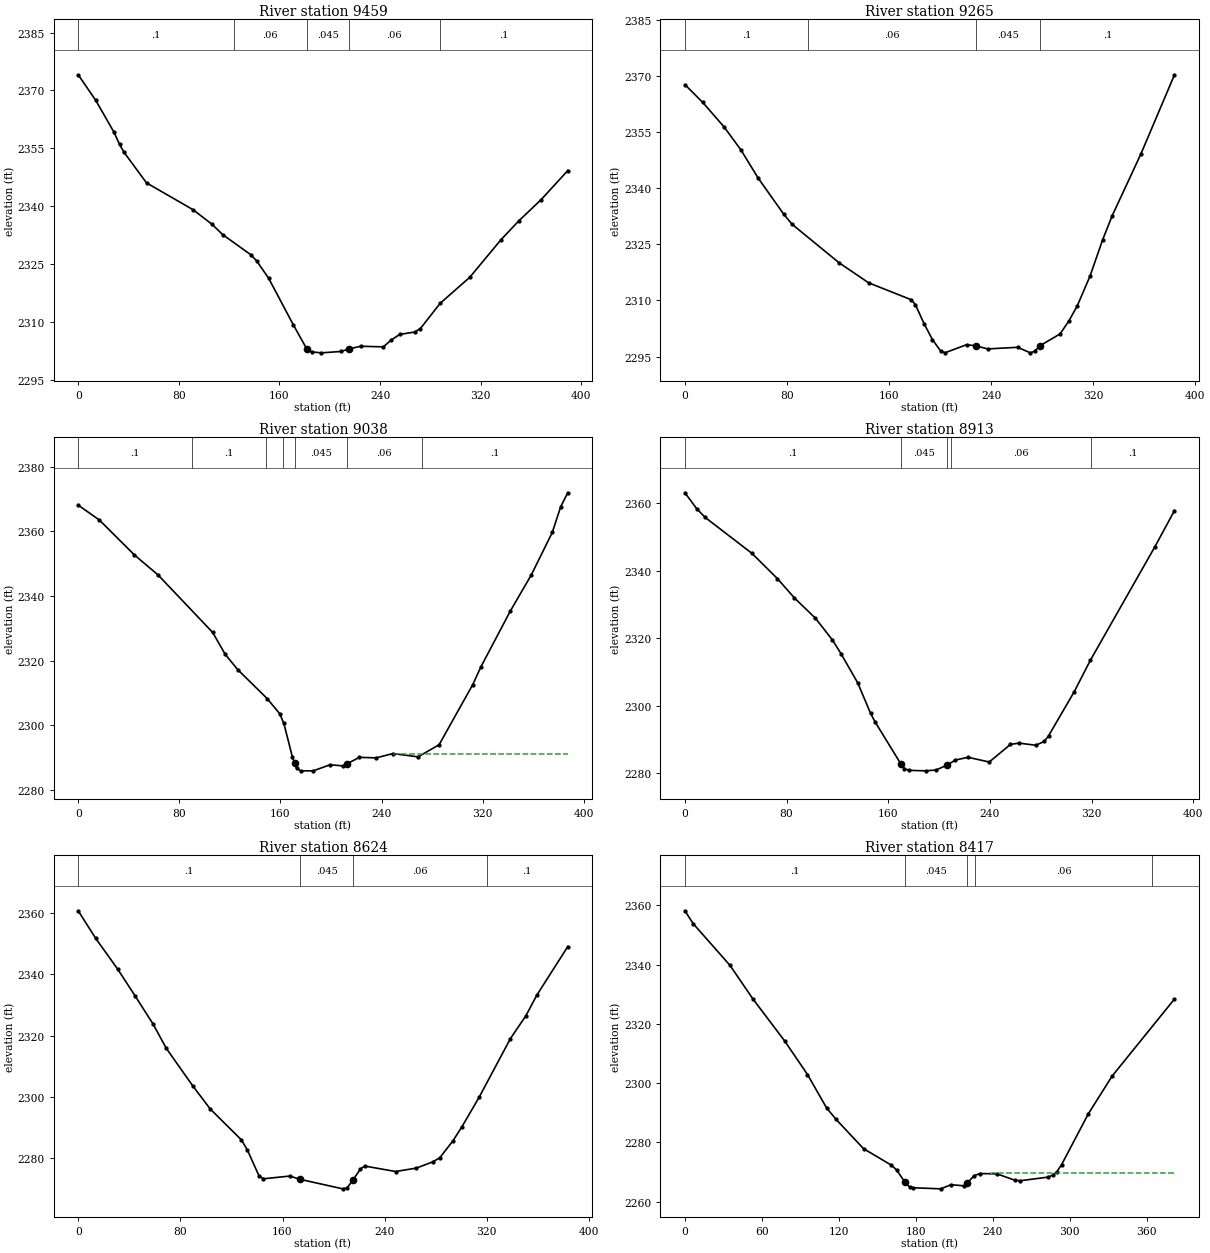
Type RM Length L Ch R = 1 ,9459    ,173.7,194.3,197.1
XS GIS Cut Line= 5
2183608.51126566363446.7060564692183608.51126566363446.706056469
2183715.53795591363609.2303554442183822.56464617363771.754654419
2183822.56464617363771.754654419
#Sta/Elev= 30
       0 2374.05      14 2367.38    28.4 2359.18    32.9 2355.97    36.3    2354
    54.3 2346.01    91.3 2339.05   106.4 2335.27   114.9 2332.58   137.2 2327.37
   141.9 2325.75   151.4 2321.27     171  2309.2   181.72302.943   185.6 2302.16
   193.4 2301.92   209.1 2302.28   215.22302.938   224.7 2303.63   242.6 2303.47
   248.4 2305.13   255.6  2306.7   267.4 2307.31     272  2308.2   287.7 2314.75
   311.3 2321.52   336.1 2331.26   350.3 2336.16   367.9 2341.62   389.2 2349.19
#Mann= 5 ,-1 , 0
       0      .1       0  123.81     .06       0   181.7    .045       0
   215.2     .06       0  287.38      .1       0
Bank Sta=181.7,215.2
XS Rating Curve= 0 ,0
Exp/Cntr=0.3,0.1

Type RM Length L Ch R = 1 ,9265    ,192.3,226.4,195.4
XS GIS Cut Line= 2
2183546.32577757363492.7943156312183615.34449685363870.305795358
#Sta/Elev= 30
       0 2367.74      14 2362.96    30.6 2356.46      44 2350.22    57.3 2342.79
    77.3 2333.14      84 2330.38   120.7 2320.12     144 2314.72   177.4  2310.2
   180.7 2308.88   187.4 2303.83     194 2299.55   200.7 2296.36   204.1 2296.03
   220.8 2298.17   227.9 2297.88   237.4 2297.04   260.8 2297.47   270.8 2295.99
   274.1 2296.43   278.6 2297.94   294.1 2301.05   301.2 2304.62   307.5 2308.51
   317.5 2316.44   327.5 2326.27     335  2332.7   357.4 2349.15   383.8 2370.37
#Mann= 4 ,-1 , 0
       0      .1       0   96.31     .06       0   227.9    .045       0
   278.6      .1       0
Bank Sta=227.9,278.6
XS Rating Curve= 0 ,0
Exp/Cntr=0.3,0.1

Type RM Length L Ch R = 1 ,9038    ,125,125.5,123.9
XS GIS Cut Line= 5
2183376.49095384363506.4175469462183376.49095384363506.417546946
2183405.57141474363697.8707988942183434.65187565363889.324050842
2183434.65187565363889.324050842
#Sta/Elev= 30
       0 2368.17    16.7 2363.56    44.4 2352.77    63.2 2346.53   106.3 2328.77
   116.3 2321.96   126.2 2317.22   149.5 2308.25   159.4 2303.57   162.7 2300.54
   169.4 2290.26   171.2 2288.28   172.7 2286.66     176 2285.87     186 2285.87
   199.2 2287.75   209.2 2287.42   212.5 2288.02   222.5 2290.05   235.7 2289.89
     249 2291.22   268.9  2290.2   285.5 2293.95   312.1 2312.55   318.7 2318.16
   341.9 2335.39   358.5 2346.59   375.1 2359.75   381.7 2367.66   387.3 2371.99
#Mann= 7 ,-1 , 0
       0      .1       0   89.75      .1       0  148.23     .06       0
   162.1     .06       0   171.2    .045       0   212.5     .06       0
  271.67      .1       0
#XS Ineff= 2 , 0
                          248.91         2291.24
Permanent Ineff=
       F       F
Bank Sta=171.2,212.5
XS Rating Curve= 0 ,0
Exp/Cntr=0.3,0.1

Type RM Length L Ch R = 1 ,8913    ,289.9,288.5,286.1
XS GIS Cut Line= 5
2183248.18455709363526.8929968112183248.18455709363526.892996811
2183283.20872712363716.3317243622183318.23289716363905.770451913
2183318.23289716363905.770451913
#Sta/Elev= 30
       0 2363.01     9.3 2358.28      16  2355.7    52.7  2345.1    72.7 2337.65
    86.1 2331.93   102.7  2325.9   116.1 2319.46   122.8 2315.43     136 2306.77
   146.1 2297.76   149.5 2295.33   169.8 2282.88   172.8 2281.42   176.1  2280.9
   189.5 2280.75   197.7    2281   206.4 2282.47   212.9 2283.96   222.9 2284.75
   239.5 2283.36   256.2 2288.57   262.9 2288.95   276.2 2288.32   282.9 2289.48
   286.3 2291.18   306.3  2304.1     319  2313.4   369.7 2346.93   385.3 2357.75
#Mann= 5 ,-1 , 0
       0      .1       0   169.8    .045       0   206.4      .1       0
  209.67     .06       0  319.67      .1       0
Bank Sta=169.8,206.4
XS Rating Curve= 0 ,0
Exp/Cntr=0.3,0.1

Type RM Length L Ch R = 1 ,8624    ,206.8,207.7,202.9
XS GIS Cut Line= 5
2182957.70384683363624.8021771512182957.70384683363624.802177151
2183017.87977327363806.8116644162183078.05569972363988.821151682
2183078.05569972363988.821151682
#Sta/Elev= 30
       0 2360.83    13.7 2351.81    30.9 2341.77    44.8 2332.85    58.6 2323.83
    68.9 2315.92    89.7 2303.59   103.5 2295.99   127.7 2285.98   132.4 2282.72
   141.5 2274.25     145 2273.21   165.7 2274.11     174 2273.01   207.2 2269.93
   210.6 2270.26   215.5 2272.98     221 2276.42   224.4 2277.38   248.6 2275.59
   264.9 2276.72   277.8 2278.76   283.2  2280.1   293.6  2285.7   300.5 2290.22
     314 2299.88   338.5 2319.05   350.6 2326.51   359.2 2333.27   383.4 2349.12
#Mann= 4 ,-1 , 0
       0      .1       0     174    .045       0   215.5     .06       0
  319.78      .1       0
Bank Sta=174,215.5
XS Rating Curve= 0 ,0
Exp/Cntr=0.3,0.1

Type RM Length L Ch R = 1 ,8417    ,188.5,182.2,176.8
XS GIS Cut Line= 5
2182752.39420599363694.2636294382182752.39420599363694.263629438
2182829.65846957363868.6640472182182906.92273314364043.064464998
2182906.92273314364043.064464998
#Sta/Elev= 30
       0 2358.17     6.4 2353.84    35.1 2339.76      53  2328.4    77.9 2314.14
    95.5 2302.92   110.4 2291.64   117.6 2287.87   139.2 2277.89   160.7 2272.38
   165.1 2270.67   171.5 2266.51     175 2265.04   177.5 2264.72   199.4 2264.35
   207.3 2265.75   217.3 2265.38   220.1 2266.36   225.3 2268.77   229.8 2269.51
   243.2 2269.41   257.1 2267.25   261.2 2267.08   282.7 2268.29     287 2269.02
   289.9  2270.2   293.5  2272.5   314.3 2289.62   332.9  2302.4   381.5 2328.41
#Mann= 5 ,-1 , 0
       0      .1       0   171.5    .045       0   220.1      .1       0
  226.22     .06       0  363.79      .1       0
#XS Ineff= 2 , 0
                          238.14         2269.61
Permanent Ineff=
       F       F
Bank Sta=171.5,220.1
XS Rating Curve= 0 ,0
Exp/Cntr=0.3,0.1

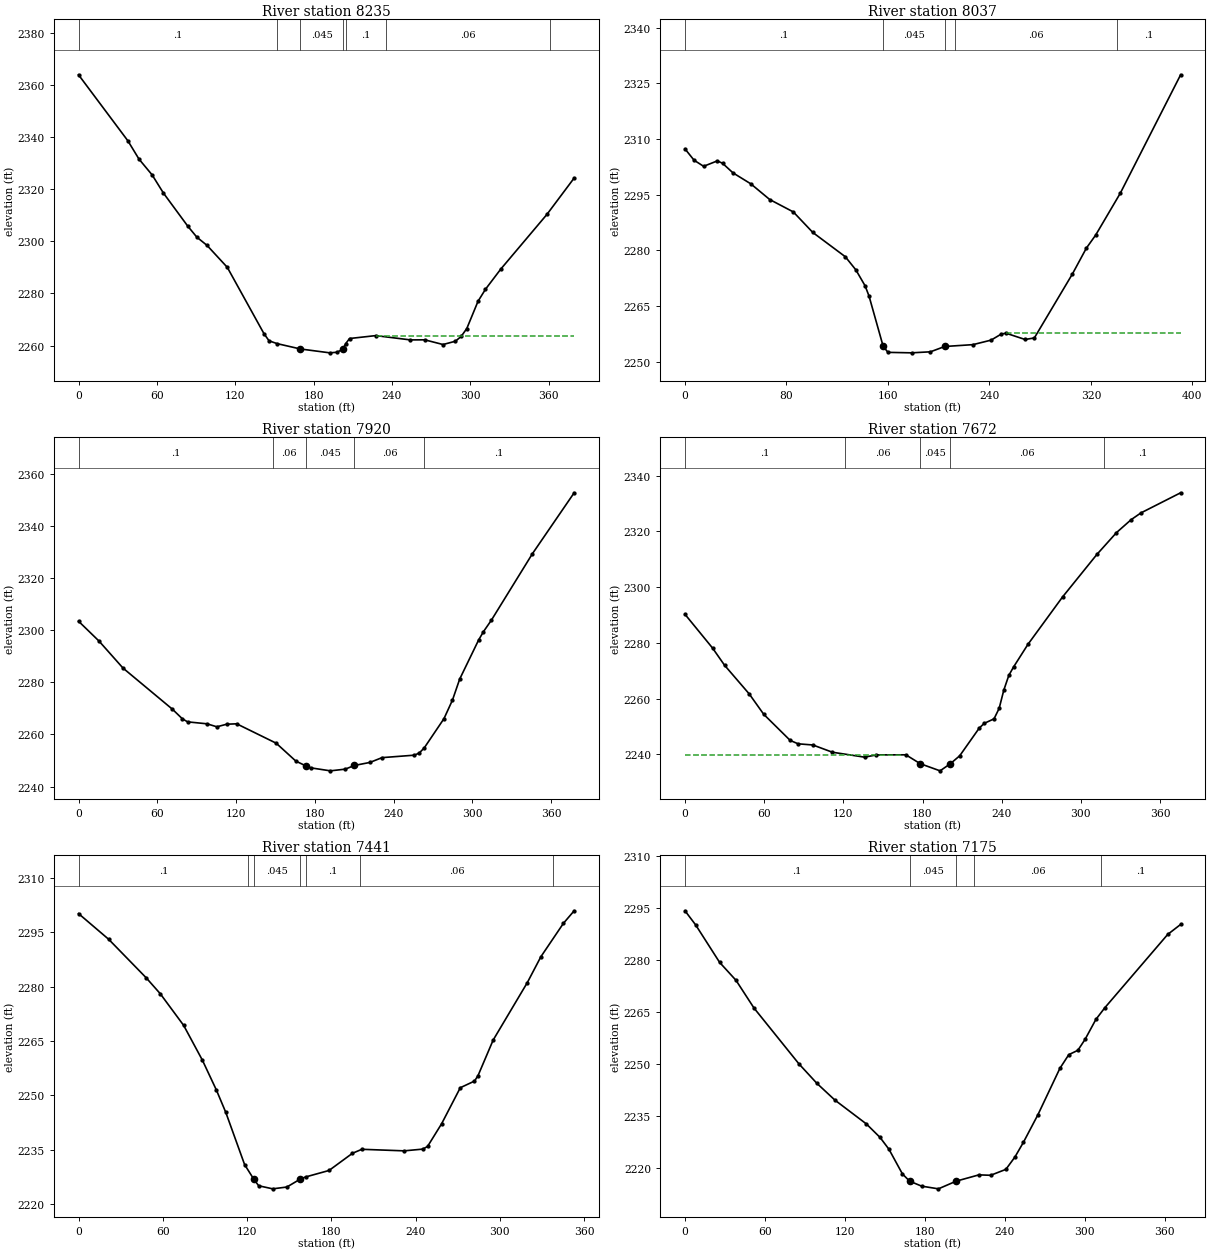
Type RM Length L Ch R = 1 ,8235    ,205.2,197.9,189.4
XS GIS Cut Line= 5
2182553.64023015363822.3138733192182553.64023015363822.313873319
2182677.24878283363966.2781080712182800.85733551364110.242342823
2182800.85733551364110.242342823
#Sta/Elev= 30
       0 2363.86    37.8 2338.53    46.3 2331.52    56.4 2325.43      65  2318.5
    83.6 2305.83    90.6 2301.57    98.4 2298.42   113.9 2290.01     142 2264.55
   145.9 2261.81   152.1 2260.73   169.9 2258.68   192.4  2257.2   197.8 2257.42
   202.2 2258.49   204.6 2260.73   207.5 2262.69   227.6 2263.81   254.1 2262.16
   265.1 2262.19   279.1 2260.39   288.6 2261.66     293 2263.51   297.3 2266.53
   305.9 2276.99   311.6 2281.59   323.2 2289.26   358.6 2310.27   379.5 2324.26
#Mann= 7 ,-1 , 0
       0      .1       0   152.1     .06       0   169.9    .045       0
   202.2     .06       0   204.6      .1       0   235.2     .06       0
   360.7      .1       0
#XS Ineff= 2 , 0
                          227.49         2263.82
Permanent Ineff=
       F       F
Bank Sta=169.9,202.2
XS Rating Curve= 0 ,0
Exp/Cntr=0.3,0.1

Type RM Length L Ch R = 1 ,8037    ,117.6,116.9,116.3
XS GIS Cut Line= 2
2182374.05328789364006.2517575862182718.10114614364191.347413851
#Sta/Elev= 30
       0 2307.36     7.2 2304.29    14.7 2302.66    25.5 2304.12    29.6 2303.48
    37.8  2300.9    51.9 2297.93    66.8  2293.7    85.4 2290.36   100.8 2284.81
   126.4 2278.27   134.7 2274.73     142 2270.42   145.1 2267.65   156.2 2254.14
     160 2252.49   178.6 2252.36   193.5 2252.64   204.7 2254.07     227 2254.57
   241.3 2255.79   249.4 2257.44   253.1 2257.65   268.1 2255.96   275.4 2256.38
   305.3 2273.57   316.4  2280.6   323.7  2284.1   343.1 2295.38   390.7 2327.34
#Mann= 5 ,-1 , 0
       0      .1       0   156.2    .045       0   204.7      .1       0
  212.81     .06       0  340.23      .1       0
#XS Ineff= 2 , 0
                          253.12          2257.7
Permanent Ineff=
       F       F
Bank Sta=156.2,204.7
XS Rating Curve= 0 ,0
Exp/Cntr=0.3,0.1

Type RM Length L Ch R = 1 ,7920    ,239.9,248,254.7
XS GIS Cut Line= 5
2182331.11615644364108.6391677852182331.11615644364108.639167785
2182495.78351315364200.9961834382182660.45086986 364293.35319909
2182660.45086986 364293.35319909
#Sta/Elev= 30
       0 2303.52    15.7 2295.84    33.9  2285.5    71.6 2269.67    79.1 2266.02
    83.1 2264.84    97.9 2264.09   105.4 2262.94   112.9 2263.94   120.5 2264.09
   150.6 2256.64   165.6 2249.75   173.1 2247.95   176.9 2247.17   191.9 2246.02
   203.2 2246.67   210.2 2248.09     222 2249.25   231.2 2251.09   255.9 2252.04
   259.6 2252.87   263.4 2254.85   278.4 2266.06   284.9 2273.22   290.4 2281.29
   304.8 2296.28   308.5  2299.5   314.5 2303.88   345.8 2329.45   377.6 2352.86
#Mann= 5 ,-1 , 0
       0      .1       0  148.07     .06       0   173.1    .045       0
   210.2     .06       0  263.52      .1       0
Bank Sta=173.1,210.2
XS Rating Curve= 0 ,0
Exp/Cntr=0.3,0.1

Type RM Length L Ch R = 1 ,7672    ,241.8,230.6,211.3
XS GIS Cut Line= 5
2182259.09598973364195.1986287692182259.09598973364195.198628769
2182346.89592926  364361.2098643 2182434.6958688364527.221099831
 2182434.6958688364527.221099831
#Sta/Elev= 30
       0 2290.25    20.9 2278.13      30 2271.96    48.7 2261.66    59.7 2254.35
    79.7    2245    85.7 2243.77    96.9 2243.35   111.7 2240.75   136.1 2238.98
   145.1 2239.79   167.4 2239.82   178.32236.628   193.3 2234.07   201.12236.623
   208.2 2239.48     223 2249.42   226.8 2251.12   234.2 2252.73   238.1 2256.52
   241.6 2263.04   245.4 2268.32     249 2271.35   259.9 2279.47   286.1 2296.46
   312.1 2311.71     327 2319.57   338.1 2324.21   345.5 2326.63   375.6 2333.86
#Mann= 5 ,-1 , 0
       0      .1       0  121.53     .06       0   178.3    .045       0
   201.1     .06       0   317.8      .1       0
#XS Ineff= 2 , 0
          165.38 2239.91
Permanent Ineff=
       F       F
Bank Sta=178.3,201.1
XS Rating Curve= 0 ,0
Exp/Cntr=0.3,0.1

Type RM Length L Ch R = 1 ,7441    ,270.6,266.2,256.3
XS GIS Cut Line= 3
2182021.43710407364434.8724044162182021.43710407364434.872404416
2182368.11147362364501.188279561
#Sta/Elev= 30
       0 2300.14    21.4 2293.08    48.1 2282.48    58.2 2278.06    74.9 2269.31
    88.2 2259.75    98.2  2251.5   104.9 2245.33   118.3 2230.94   124.7 2227.01
   128.3 2225.12   138.3 2224.27   148.4 2224.77   157.9 2226.95   161.7 2227.54
   178.4 2229.33   195.1 2234.07   201.8 2235.17   231.9 2234.74   245.2 2235.22
   248.6 2235.96   258.6 2242.21   271.9 2252.14     282 2253.97   284.5 2255.45
   295.3 2265.27   319.6 2281.09   329.3 2288.25   345.4 2297.48     353 2300.91
#Mann= 7 ,-1 , 0
       0      .1       0   120.9     .06       0   124.7    .045       0
   157.9     .06       0   161.7      .1       0  200.68     .06       0
  337.74      .1       0
Bank Sta=124.7,157.9
XS Rating Curve= 0 ,0
Exp/Cntr=0.3,0.1

Type RM Length L Ch R = 1 ,7175    ,231.4,230.4,224.9
XS GIS Cut Line= 5
2182038.01078772 364759.303483612182038.01078772 364759.30348361
2182218.82212522364716.1086669482182399.63346272364672.913850286
2182399.63346272364672.913850286
#Sta/Elev= 30
       0 2294.26       8 2290.18      26 2279.33    38.3 2274.14    51.8 2266.12
    85.5 2249.98      99 2244.34   112.5  2239.5   136.1 2232.61   146.3 2228.73
     153  2225.3   163.1 2218.17   168.52216.072   177.5 2214.63   190.1 2213.85
   203.42216.066   220.5 2217.89   229.3 2217.77   240.7 2219.48   247.5 2223.05
   253.8 2227.26   264.7 2235.24   281.2 2248.67   287.9 2252.65   294.7 2253.91
   300.1 2257.06   308.2 2262.82   314.9  2266.2   362.1 2287.42   371.8 2290.31
#Mann= 5 ,-1 , 0
       0      .1       0   168.5    .045       0   203.4      .1       0
  217.07     .06       0  312.22      .1       0
Bank Sta=168.5,203.4
XS Rating Curve= 0 ,0
Exp/Cntr=0.3,0.1

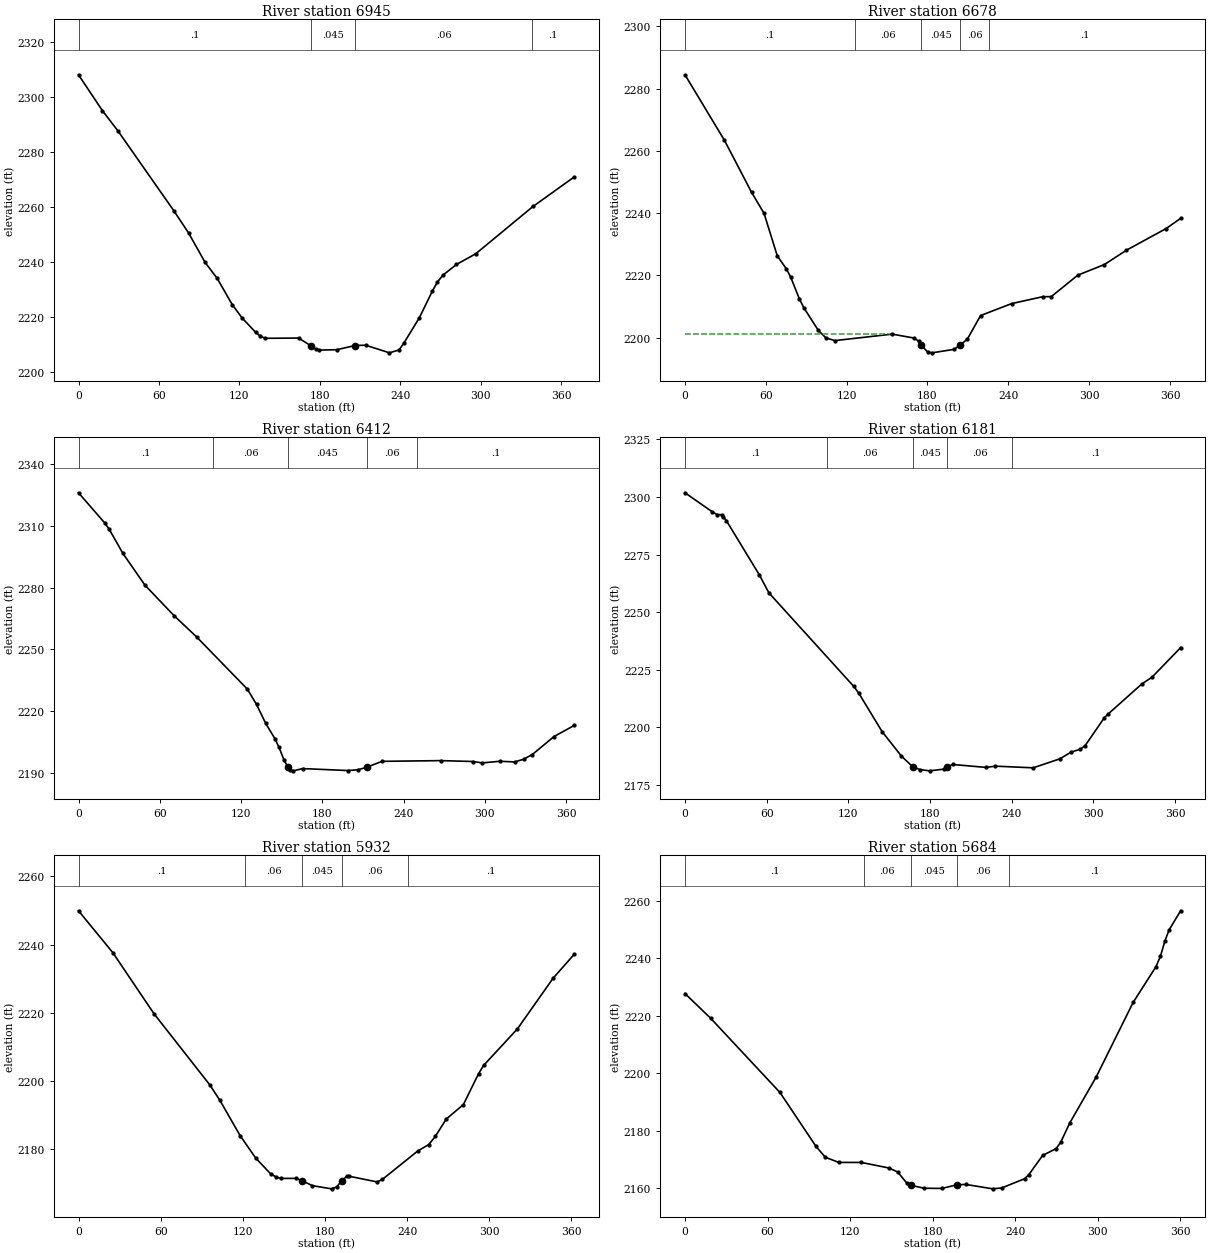
Type RM Length L Ch R = 1 ,6945    ,263.1,266.7,273.4
XS GIS Cut Line= 5
2182117.94598709365005.1924602332182117.94598709365005.192460233
2182287.88974901364932.3443119322182457.83351093364859.496163631
2182457.83351093364859.496163631
#Sta/Elev= 30
       0 2307.98    17.8 2294.94    29.5 2287.51    71.4  2258.3    82.1 2250.43
    94.4 2239.74   103.5 2233.86   114.8 2224.26   121.9 2219.59   132.1 2214.28
   135.6 2212.89   139.2 2212.09   164.2 2212.18   173.1 2209.45   176.9 2208.16
   179.4  2207.8   192.7 2207.94   206.4 2209.47   214.2 2209.58     232  2206.8
   239.2 2207.88   242.7 2210.31   254.3 2219.57   264.1 2229.37   267.7 2232.49
   271.8 2235.02     282 2238.97   296.3 2242.82   339.1 2260.07   369.8 2270.78
#Mann= 4 ,-1 , 0
       0      .1       0   173.1    .045       0   206.4     .06       0
   338.1      .1       0
Bank Sta=173.1,206.4
XS Rating Curve= 0 ,0
Exp/Cntr=0.3,0.1

Type RM Length L Ch R = 1 ,6678    ,263.1,266.3,266.3
XS GIS Cut Line= 5
2182197.05191247365166.4240104722182197.05191247365166.424010472
2182380.99566292365164.9999218242182564.93941336365163.575833176
2182564.93941336365163.575833176
#Sta/Elev= 30
       0 2284.44    29.2 2263.46    49.4 2246.71    58.7 2239.91    68.5 2226.28
    75.1 2222.19    78.4 2219.52    84.9 2212.45    88.2 2209.62      99 2202.31
   104.6 2199.94   111.2 2199.05   153.8 2201.13   170.2 2199.86   173.5 2198.84
   175.2 2197.68   180.1  2195.4   183.4 2195.12   199.8 2196.25   204.5  2197.7
   209.6 2199.54   219.4 2207.09   242.4 2210.93   265.4 2213.14   271.9 2213.19
   291.6 2220.08   311.3 2223.48   327.7 2228.09   357.2 2235.06   367.9 2238.32
#Mann= 5 ,-1 , 0
       0      .1       0  126.17     .06       0   175.2    .045       0
   204.5     .06       0  226.01      .1       0
#XS Ineff= 2 , 0
          152.01 2201.09
Permanent Ineff=
       F       F
Bank Sta=175.2,204.5
XS Rating Curve= 0 ,0
Exp/Cntr=0.3,0.1

Type RM Length L Ch R = 1 ,6412    ,228,230.3,229.4
XS GIS Cut Line= 5
2182142.10776529365364.2735520742182142.10776529365364.273552074
2182318.58821692365412.4926819222182495.06866855365460.711811769
2182495.06866855365460.711811769
#Sta/Elev= 30
       0 2326.17    19.2 2311.61    22.6 2308.51    32.8 2296.65    49.1  2281.2
    70.5 2266.44    87.2 2256.05   124.6 2230.71   131.4 2223.24   138.2 2214.01
     145 2206.56     148 2202.39   151.8 2196.05   154.42192.943     156 2191.59
   158.6 2190.94   165.4 2192.04   198.7 2191.09   206.2 2191.44     213 2192.73
     224 2195.56   267.4 2195.91   291.2 2195.48     298 2194.79   310.9 2195.59
   321.9 2195.28   328.7  2196.6     335 2198.88     351  2207.6   365.9 2213.02
#Mann= 5 ,-1 , 0
       0      .1       0   99.61     .06       0   154.4    .045       0
     213     .06       0   249.8      .1       0
Bank Sta=154.4,213
XS Rating Curve= 0 ,0
Exp/Cntr=0.3,0.1

Type RM Length L Ch R = 1 ,6181    ,234.4,248.8,255.9
XS GIS Cut Line= 5
 2182085.8962053365570.968399606 2182085.8962053365570.968399606
2182258.14257004365629.7470139792182430.38893478365688.525628352
2182430.38893478365688.525628352
#Sta/Elev= 30
       0 2301.79      20 2293.56    23.5 2292.33    26.9 2292.27      28 2291.49
    30.4 2289.71    54.7  2266.1    61.6 2258.41     124 2217.79   127.5 2215.01
   144.8 2198.17     159 2187.57   167.32182.948   172.5 2181.73   179.7  2181.2
   189.9 2181.92   192.6 2183.04   196.8 2183.95     221 2182.69     228 2183.23
   255.7 2182.51   275.3  2186.4   283.5 2189.31   290.4  2190.6   293.9 2192.16
   307.7 2204.01   310.5 2205.71   335.4 2218.83     343 2221.82     364 2234.64
#Mann= 5 ,-1 , 0
       0      .1       0  104.08     .06       0   167.3    .045       0
   192.6     .06       0  240.05      .1       0
Bank Sta=167.3,192.6
XS Rating Curve= 0 ,0
Exp/Cntr=0.3,0.1

Type RM Length L Ch R = 1 ,5932    ,240.3,248.5,252.5
XS GIS Cut Line= 5
2182037.89048977365659.1932215092182037.89048977365659.193221509
2182121.97069714365819.4781468752182206.05090451 365979.76307224
2182206.05090451 365979.76307224
#Sta/Elev= 30
       0 2249.94      25 2237.69    55.1 2219.75    95.8  2198.9   103.3 2194.29
   118.1 2183.92   129.4 2177.39   140.3 2172.75     144  2171.9   147.7 2171.41
   158.8 2171.42   163.5 2170.71   170.8 2169.28   184.8 2168.35   188.5  2168.9
   192.2 2170.69   195.9 2172.06   197.5 2172.06   218.1 2170.37   221.9 2171.11
   247.7 2179.44   255.8 2181.33   260.7  2183.8   268.6 2188.83   281.1 2193.08
   292.2 2202.15   295.9 2204.58   320.6 2215.31   346.5 2230.09     362 2237.16
#Mann= 5 ,-1 , 0
       0      .1       0  121.27     .06       0   163.5    .045       0
   192.2     .06       0  240.58      .1       0
Bank Sta=163.5,192.2
XS Rating Curve= 0 ,0
Exp/Cntr=0.3,0.1

Type RM Length L Ch R = 1 ,5684    ,195.2,198,200
XS GIS Cut Line= 5
2181871.25748307365681.8697585762181871.25748307365681.869758576
2181885.14345201365861.3827797572181899.02942095366040.895800938
2181899.02942095366040.895800938
#Sta/Elev= 30
       0 2227.66    18.8 2218.99      69 2193.27    95.1 2174.58   101.9 2170.76
   111.7 2168.96   128.2 2168.94   147.9 2167.04   154.5 2165.65   161.1 2161.79
     1642161.008   173.9 2159.97   186.8 2159.92   197.3 2161.15   203.9 2161.31
   223.6 2159.77   230.2  2160.1   246.7 2163.27   249.9 2164.74   259.8 2171.36
   269.7 2173.78     273    2176   279.6  2182.7   298.8 2198.71   325.6 2224.58
   342.1 2236.93   345.4 2240.56   348.6 2245.81   351.7 2249.77   360.1 2256.43
#Mann= 5 ,-1 , 0
       0      .1       0  129.99     .06       0     164    .045       0
   197.3     .06       0  235.46      .1       0
Bank Sta=164,197.3
XS Rating Curve= 0 ,0
Exp/Cntr=0.3,0.1

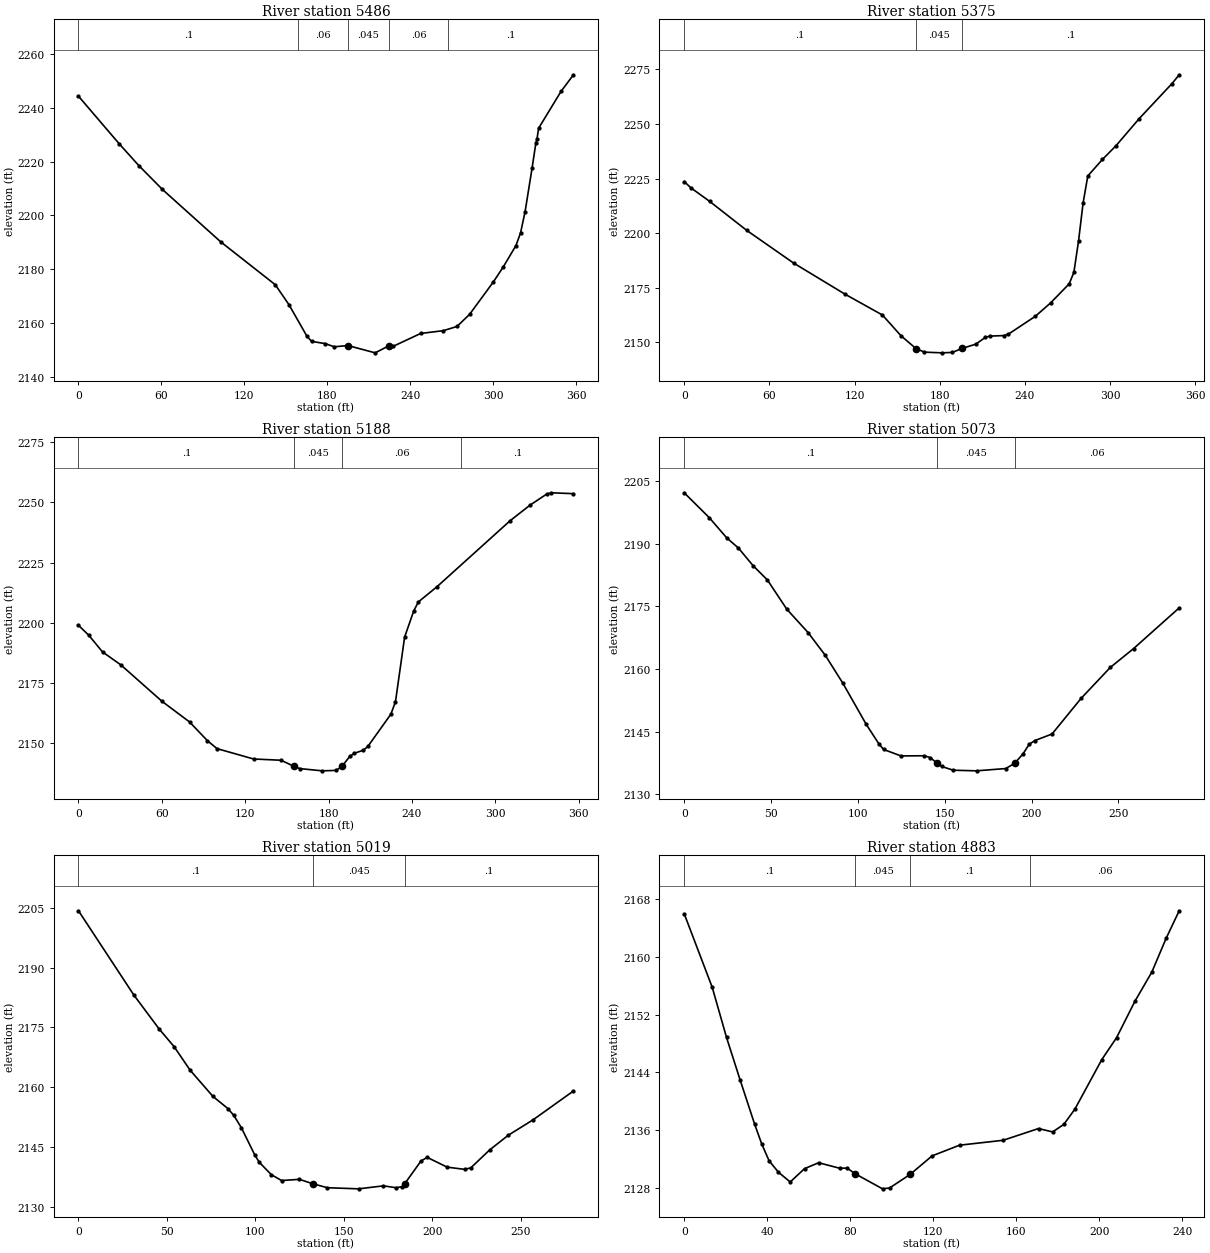
Type RM Length L Ch R = 1 ,5486    ,109.6,110.9,110
XS GIS Cut Line= 5
2181701.94688453365631.4134769832181701.94688453365631.413476983
2181691.62622121365810.215155179 2181681.3055579365989.016833375
 2181681.3055579365989.016833375
#Sta/Elev= 30
       0 2244.28    29.6 2226.53    43.8 2218.44    60.7 2209.68     103 2190.17
   142.4 2174.29   152.3 2166.89   165.4 2155.08   168.7 2153.25   178.6 2152.41
   185.1 2151.24     195 2151.69   214.7 2148.99   224.6  2151.6   227.9 2151.45
   247.6 2156.18     264 2157.22   273.9 2158.78     283 2163.26   300.2 2175.29
   307.4 2180.89   316.6 2188.83   319.9 2193.51   323.2 2201.43   328.3 2217.75
     331 2226.93   331.8  2228.4     333  2232.4   349.2 2246.05   358.2 2252.23
#Mann= 5 ,-1 , 0
       0      .1       0  159.21     .06       0     195    .045       0
   224.6     .06       0  267.71      .1       0
Bank Sta=195,224.6
XS Rating Curve= 0 ,0
Exp/Cntr=0.3,0.1

Type RM Length L Ch R = 1 ,5375    ,187.8,186.9,182.6
XS GIS Cut Line= 2
2181596.29318689365644.1920427642181569.61926987365992.019920619
#Sta/Elev= 30
       0  2223.6     4.7 2220.73    17.9 2214.53    44.1 2201.19    77.1 2186.23
   113.3 2171.97   139.7  2162.4   152.8 2152.88   163.3 2147.04   169.3 2145.39
   181.7 2145.07     189 2145.27   195.6 2147.06   205.5 2149.05   212.2 2152.18
   215.4 2152.75   225.2 2152.98   228.5 2153.66   247.5 2161.86   258.2 2167.97
   271.3 2176.72   274.6 2182.01   277.9 2196.49   281.1 2213.84   284.4 2226.17
   294.7 2233.74   304.2 2239.98   320.6 2252.45   343.7  2268.5   348.8 2272.56
#Mann= 3 , 0 , 0
       0      .1       0   163.3    .045       0   195.6      .1       0
Bank Sta=163.3,195.6
XS Rating Curve= 0 ,0
Exp/Cntr(USF)=0,0
Exp/Cntr=0.3,0.1

Type RM Length L Ch R = 1 ,5188    ,116.4,115.6,111.6
XS GIS Cut Line= 5
2181384.84267545365657.9352895462181384.84267545365657.935289546
2181400.86805909365835.3121373432181416.89344273366012.688985139
2181416.89344273366012.688985139
#Sta/Elev= 30
       0 2198.95     7.4 2194.83    17.3  2187.9    30.5  2182.5    60.1 2167.36
    79.9  2158.8    92.8    2151    99.7  2147.7     126  2143.4   145.8 2142.87
   155.32140.279   159.2 2139.41   175.4 2138.47   185.3 2138.65   189.62140.291
   195.2 2144.46   198.5 2145.78   205.1 2147.05   208.4 2148.74   224.8    2162
   228.1 2167.15   234.7 2194.06   241.3    2205   244.6 2208.68   257.8  2214.9
   310.7 2242.47   325.2 2249.01   336.8 2253.44   340.1 2254.04   356.2 2253.67
#Mann= 4 ,-1 , 0
       0      .1       0   155.3    .045       0   189.6     .06       0
  275.43      .1       0
Bank Sta=155.3,189.6
XS Rating Curve= 0 ,0
Exp/Cntr=0.3,0.1

Type RM Length L Ch R = 1 ,5073    ,58.5,53.9,49.7
XS GIS Cut Line= 2
2181255.44582762365674.1373852552181311.18209573365953.602339224
#Sta/Elev= 30
       0 2202.17    14.4 2196.23    24.5 2191.37    31.2 2188.95    39.6 2184.75
    47.9  2181.3    59.1 2174.29    71.3 2168.72    81.3 2163.22    91.4 2156.55
   104.8 2146.74   112.1 2142.06   114.8 2140.73   124.8 2139.18   138.2 2139.22
   141.6 2138.79   145.6 2137.47   148.3 2136.65   154.9 2135.76   168.3 2135.61
   185.1 2136.16   190.2 2137.38   195.1 2139.68   198.6 2141.95   201.8 2142.84
   211.8 2144.43   228.5 2152.95   245.3 2160.35   258.7 2164.86     285 2174.62
#Mann= 3 ,-1 , 0
       0      .1       0   145.6    .045       0   190.2     .06       0
Bank Sta=145.6,190.2
XS Rating Curve= 0 ,0
Exp/Cntr=0.3,0.1

Type RM Length L Ch R = 1 ,5019    ,147.7,136.1,111.7
XS GIS Cut Line= 2
2181178.04616812365705.0085735542181280.47400945365965.346003605
#Sta/Elev= 30
       0 2204.23    31.3 2183.11    45.5 2174.66    54.1 2170.14    63.1 2164.28
      76  2157.7    84.5 2154.64    87.8 2152.94    92.1 2149.83    99.6 2143.07
   102.2 2141.18     109 2138.09   114.8 2136.61   124.9 2136.91   132.5  2135.8
   140.7 2134.81   158.3 2134.53   172.4 2135.28   179.5 2134.81     183 2135.08
   184.32135.739   193.6  2141.5   197.1 2142.42   208.4 2139.97   218.3 2139.41
   221.8  2139.8   232.4 2144.27   242.9 2147.95     257 2151.84   279.8 2159.06
#Mann= 3 , 0 , 0
       0      .1       0   132.5    .045       0   184.3      .1       0
Bank Sta=132.5,184.3
XS Rating Curve= 0 ,0
Exp/Cntr(USF)=0,0
Exp/Cntr=0.3,0.1

Type RM Length L Ch R = 1 ,4883    ,106,100.5,92.3
XS GIS Cut Line= 2
 2181061.6518833365907.4037524432181290.66854274365974.330995386
#Sta/Elev= 30
       0 2165.98    13.5 2155.78    20.4 2148.83    26.9 2142.98      34 2136.76
    37.4 2134.04    40.9 2131.74    45.4 2130.15    51.1 2128.79      58 2130.64
    64.8 2131.46      75 2130.69    78.5 2130.72    82.4 2129.93    95.6 2127.84
      99 2127.96   108.9 2129.84   119.5 2132.41   132.7 2133.89   153.7 2134.57
   170.8  2136.2   177.6 2135.73     183 2136.78   188.3 2138.88   201.3 2145.76
   208.4 2148.79   217.3 2153.87   225.4 2157.88   232.3 2162.57   238.6 2166.39
#Mann= 4 ,-1 , 0
       0      .1       0    82.4    .045       0   108.9      .1       0
  166.69     .06       0
Bank Sta=82.4,108.9
XS Rating Curve= 0 ,0
Exp/Cntr=0.3,0.1

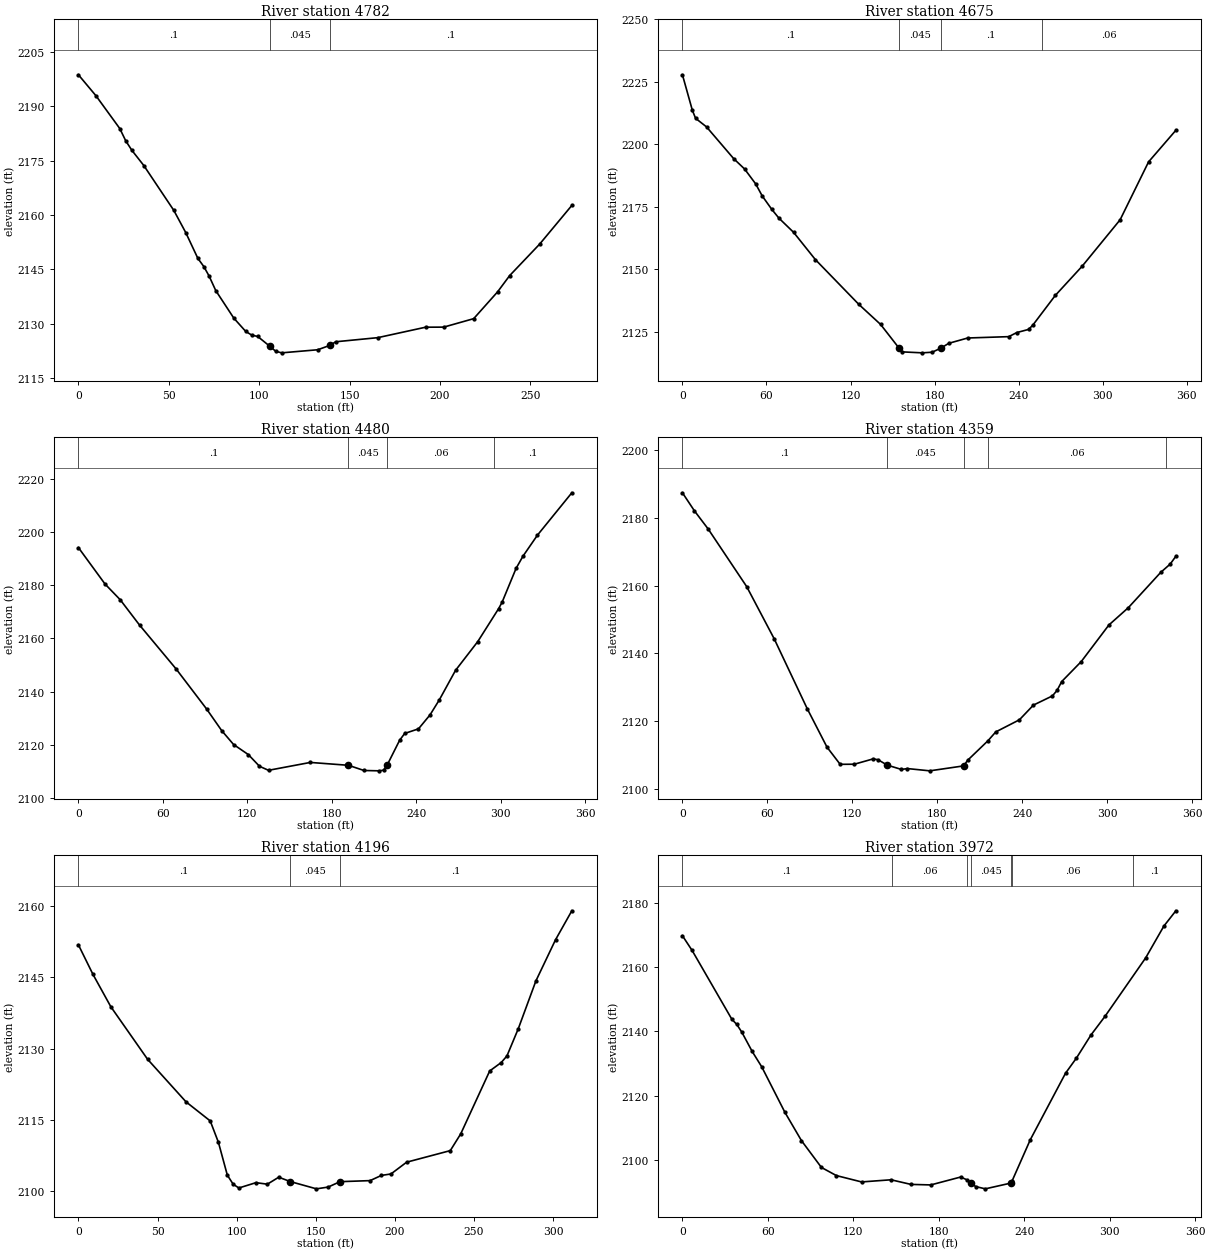
Type RM Length L Ch R = 1 ,4782    ,111.5,106.6,98.5
XS GIS Cut Line= 2
2181015.86875267366049.6355813682181285.80879285366009.091227507
#Sta/Elev= 30
       0 2198.69     9.7 2192.91    22.9 2183.84    26.2 2180.44    29.6 2177.82
    36.2 2173.62    52.8 2161.23    59.4  2155.1    66.1 2147.98    69.4 2145.72
    72.3 2143.12      76 2139.09      86 2131.47    92.6  2127.8    95.9  2126.8
    99.2 2126.42   105.9 2123.72   109.2 2122.31   112.5  2121.9   132.4 2122.75
     139 2123.94   142.4 2124.96   165.6 2126.09   192.1 2128.98   202.1    2129
   218.7 2131.34   231.9 2138.73   238.6 2143.23   255.2 2151.93     273 2162.61
#Mann= 3 , 0 , 0
       0      .1       0   105.9    .045       0     139      .1       0
Bank Sta=105.9,139
XS Rating Curve= 0 ,0
Exp/Cntr(USF)=0,0
Exp/Cntr=0.3,0.1

Type RM Length L Ch R = 1 ,4675    ,190.5,195.5,193.8
XS GIS Cut Line= 5
2181043.69374943366211.7931578752181043.69374943366211.793157875
2181192.44947593366117.4517217082181341.20520242366023.110285542
2181341.20520242366023.110285542
#Sta/Elev= 30
       0 2227.75     7.1 2213.52     9.4 2210.33    17.2  2206.9    36.6 2194.19
    44.4 2190.04    52.3 2184.09      57 2179.24    63.8  2173.9    68.9 2170.38
    79.4 2164.69    94.9 2153.81     126 2135.85   141.5 2127.85   154.5 2118.49
   157.1 2116.87   171.2 2116.49   178.3 2116.74   184.3 2118.31   190.2 2120.31
   203.7 2122.43     233 2122.97   238.7  2124.6   247.2 2125.87   250.3 2127.67
   266.2 2139.45   285.3 2151.09   312.5 2169.73   332.8 2192.89   352.3 2205.54
#Mann= 4 ,-1 , 0
       0      .1       0   154.5    .045       0   184.3      .1       0
  256.38     .06       0
Bank Sta=154.5,184.3
XS Rating Curve= 0 ,0
Exp/Cntr=0.3,0.1

Type RM Length L Ch R = 1 ,4480    ,118.8,120.6,122.5
XS GIS Cut Line= 5
2181142.74911048366332.2649505282181142.74911048366332.264950528
2181302.11317663366259.4783555472181461.47724278366186.691760566
2181461.47724278366186.691760566
#Sta/Elev= 30
       0 2194.15    18.9 2180.45    29.7 2174.53    43.4 2165.02    69.4  2148.5
      91 2133.48   101.8 2125.29   110.2 2120.09   120.7 2116.29   128.6  2111.9
     135 2110.39   164.7 2113.35   191.8 2112.27   202.8 2110.32   213.7 2110.19
   216.7 2110.45   219.2 2112.29   228.1 2121.68   231.7 2124.25   241.5 2125.98
   249.7 2131.23   256.3 2136.88   267.8 2147.97   283.6  2158.8   298.4 2171.18
   300.9 2173.63   310.8 2186.33   315.7 2190.92     326 2198.84   350.4 2214.76
#Mann= 4 ,-1 , 0
       0      .1       0   191.8    .045       0   219.2     .06       0
  295.35      .1       0
Bank Sta=191.8,219.2
XS Rating Curve= 0 ,0
Exp/Cntr=0.3,0.1

Type RM Length L Ch R = 1 ,4359    ,158.2,163.9,157.7
XS GIS Cut Line= 5
2181168.25793629366395.4130223622181168.25793629366395.413022362
2181339.94895026366365.6638050972181511.63996423366335.914587832
2181511.63996423366335.914587832
#Sta/Elev= 30
       0 2187.35     8.5 2182.01    18.2 2176.67    45.4 2159.69    64.8 2144.33
    88.1 2123.76   102.1  2112.4   111.4 2107.33   121.4 2107.36   134.7 2108.93
   138.1 2108.69   144.7 2107.09   154.7 2105.82   158.9 2106.08   174.7 2105.41
   198.6 2106.87   201.5 2108.55   215.7 2114.24   221.3 2116.88     238 2120.45
   247.9 2124.78   261.3 2127.49   264.6 2129.12   267.9 2131.73   281.7 2137.62
   301.2 2148.39     315 2153.52   337.8 2163.89   344.5 2166.34   348.5 2168.64
#Mann= 5 ,-1 , 0
       0      .1       0   144.7    .045       0   198.6     .06       0
   215.7     .06       0  341.71      .1       0
Bank Sta=144.7,198.6
XS Rating Curve= 0 ,0
Exp/Cntr=0.3,0.1

Type RM Length L Ch R = 1 ,4196    ,211.2,223.5,233.5
XS GIS Cut Line= 2
2181218.59052198366559.640874665  2181502.400999 366430.53911632
#Sta/Elev= 30
       0 2151.83     9.2 2145.61    20.5 2138.79    43.7 2127.74      68 2118.77
    83.3 2114.75    88.5 2110.22    94.1 2103.34    97.8 2101.42   101.4 2100.63
   112.2 2101.75   119.4 2101.43   126.6  2102.9   133.8 2101.99   150.4 2100.45
   157.8 2100.82   165.3 2101.96   184.3 2102.18   191.5 2103.28   197.5 2103.58
   207.4 2106.06     235  2108.5   241.6 2112.03   259.9 2125.27   267.2 2127.05
   270.8 2128.44     278  2134.2   289.1 2144.24   301.5  2152.9   311.8    2159
#Mann= 3 , 0 , 0
       0      .1       0   133.8    .045       0   165.3      .1       0
Bank Sta=133.8,165.3
XS Rating Curve= 0 ,0
Exp/Cntr(USF)=0,0
Exp/Cntr=0.3,0.1

Type RM Length L Ch R = 1 ,3972    ,224.2,224.2,208.1
XS GIS Cut Line= 5
2181186.39711859366635.6914644632181186.39711859366635.691464463
2181349.11272937366695.1805641952181511.82834016366754.669663927
2181511.82834016366754.669663927
#Sta/Elev= 30
       0 2169.79     6.8 2165.21    34.7 2143.79    38.2 2142.16    41.7 2139.77
      49 2133.75    55.7 2128.97      72 2114.78    83.6 2105.99    97.6 2097.65
   108.1 2095.12   125.8 2093.14   146.5 2093.81   160.5 2092.37   174.4 2092.21
   195.4 2094.67   199.9 2093.77   202.9 2092.78   205.9  2091.7   212.7 2090.99
   230.6 2092.78   231.5 2093.45   244.3  2106.3     269 2126.97   276.7 2131.72
   286.9  2138.9   296.7 2144.67   325.3  2162.9   338.1 2172.81   346.5 2177.56
#Mann= 7 ,-1 , 0
       0      .1       0  147.14     .06       0   199.9     .06       0
   202.9    .045       0   230.6     .06       0   231.5     .06       0
  316.49      .1       0
Bank Sta=202.9,230.6
XS Rating Curve= 0 ,0
Exp/Cntr=0.3,0.1