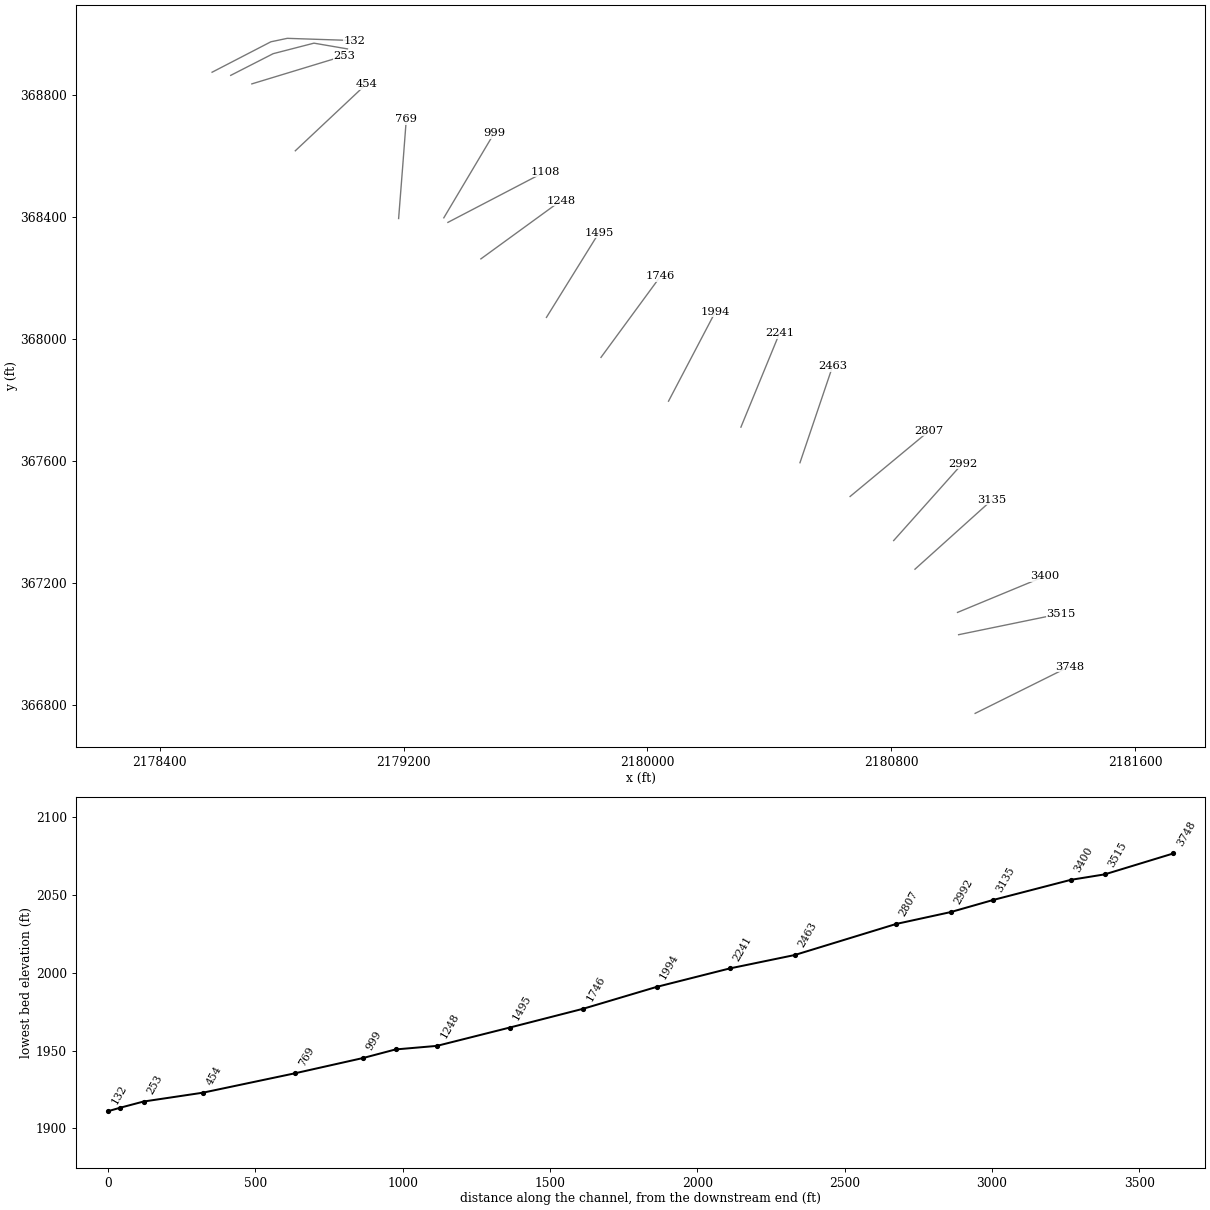
HEC-RAS study SLBCMPRN.prj: SLBCMPRN

--- SLBCMPRN.g02 (geometry) --- (continued)

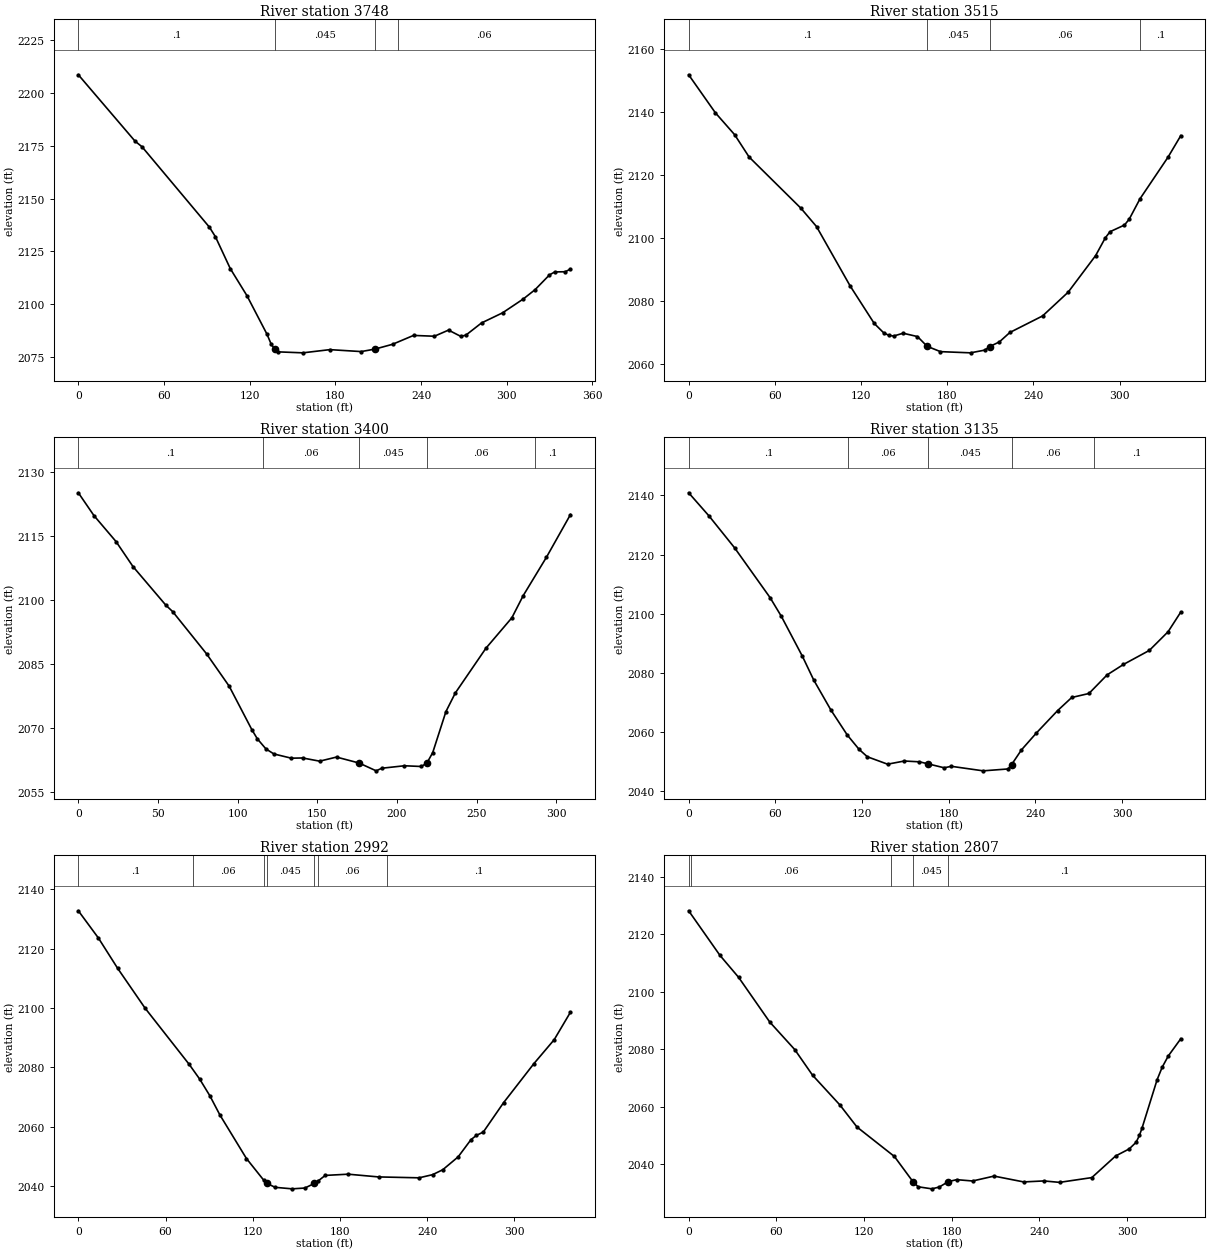
Type RM Length L Ch R = 1 ,3748    ,233.5,233.2,210.9
XS GIS Cut Line= 5
2181074.46498535366773.7063714882181074.46498535366773.706371488
2181228.75011577366850.4080838782181383.03524618366927.109796269
2181383.03524618366927.109796269
#Sta/Elev= 30
       0 2208.72    39.7 2177.25    44.6 2174.58    91.8 2136.45      96 2131.92
   106.4 2116.81     118 2104.06   132.1 2085.71   135.1  2080.9   137.6 2078.61
   137.6 2078.59     140 2077.35   157.2 2076.89   176.1 2078.41     198 2077.49
   207.6 2078.65     220 2080.94   234.7 2085.15   249.3 2084.76   259.2 2087.67
   267.7 2084.72   271.3 2085.25   282.3 2091.06     297 2095.84   311.6 2102.45
   319.8 2106.84   329.9 2113.85   333.6 2115.25   340.9 2115.34   344.6 2116.61
#Mann= 4 ,-1 , 0
       0      .1       0   137.6    .045       0   207.6      .1       0
  223.95     .06       0
Bank Sta=137.6,207.6
XS Rating Curve= 0 ,0
Exp/Cntr=0.3,0.1

Type RM Length L Ch R = 1 ,3515    ,113.8,115,119.6
XS GIS Cut Line= 5
2181020.27502071367031.6999196282181020.27502071367031.699919628
 2181188.0640873367066.2004416352181355.85315389367100.700963643
2181355.85315389367100.700963643
#Sta/Elev= 30
       0 2151.76    18.6 2139.68      32 2132.73    42.1 2125.62    78.1 2109.38
      89 2103.54   112.4 2084.68   129.2 2072.74   135.9 2069.71   139.2 2069.02
   142.6 2068.74   149.3 2069.64   159.3 2068.58     166 2065.49   175.3 2063.79
   196.2 2063.41   206.2 2064.28   209.6 2065.42   216.3 2066.88   223.6 2069.88
   246.4 2075.14   264.2 2082.69   283.3 2094.31     290 2099.91   293.3 2101.89
   303.4 2104.02   306.7 2105.89   314.2 2112.36   333.7 2125.58   342.6 2132.43
#Mann= 4 ,-1 , 0
       0      .1       0     166    .045       0   209.6     .06       0
  314.29      .1       0
Bank Sta=166,209.6
XS Rating Curve= 0 ,0
Exp/Cntr=0.3,0.1

Type RM Length L Ch R = 1 ,3400    ,259.1,264.9,274.2
XS GIS Cut Line= 2
2181016.68514194367104.7739582252181302.17166262367222.942371547
#Sta/Elev= 30
       0 2125.14     9.8 2119.79    23.7 2113.68    34.3 2107.83      55 2098.74
    59.2 2097.27    80.5 2087.35    94.7 2079.76   108.9 2069.58   112.4 2067.39
   117.8 2065.03   122.8 2063.85   133.7 2062.86   140.8 2062.91   151.5 2062.16
   162.1 2063.12   176.3 2061.72     187 2059.89   190.5  2060.5   204.7 2061.08
   215.4 2060.91   218.9 2061.75   222.5 2064.17   230.8  2073.8   236.7 2078.17
   255.9 2088.66   272.2 2095.81   279.3    2101   293.9 2110.01     309 2120.04
#Mann= 5 ,-1 , 0
       0      .1       0  116.02     .06       0   176.3    .045       0
   218.9     .06       0  286.56      .1       0
Bank Sta=176.3,218.9
XS Rating Curve= 0 ,0
Exp/Cntr=0.3,0.1

Type RM Length L Ch R = 1 ,3135    ,133.7,142.9,144.3
XS GIS Cut Line= 5
2180877.12147622367246.4773095152180877.12147622367246.477309515
2181003.76029573367360.4137058242181130.39911523367474.350102133
2181130.39911523367474.350102133
#Sta/Elev= 30
       0 2140.88    14.1 2133.04    31.8 2122.27    56.4 2105.41    64.1 2099.17
    78.8 2085.55    86.6 2077.56    98.4 2067.49   109.8 2058.99     118 2054.12
   123.7 2051.63   137.7 2049.12   149.3 2050.19   159.8 2049.92   165.6 2049.25
   176.9  2047.9   181.8  2048.4   203.9 2046.87   221.1 2047.51   223.52048.941
   230.4 2053.96   240.7 2059.65   255.4 2067.23   265.2 2071.67   277.1 2073.02
   289.7 2079.32     301 2082.84   318.9 2087.58   331.9  2093.9   340.7 2100.56
#Mann= 5 ,-1 , 0
       0      .1       0  110.54     .06       0   165.6    .045       0
   223.5     .06       0  280.33      .1       0
Bank Sta=165.6,223.5
XS Rating Curve= 0 ,0
Exp/Cntr=0.3,0.1

Type RM Length L Ch R = 1 ,2992    ,188.4,185.1,183.2
XS GIS Cut Line= 5
  2180807.297528 367340.36960351  2180807.297528 367340.36960351
2180920.05910917367466.7184124432181032.82069035367593.067221375
2181032.82069035367593.067221375
#Sta/Elev= 30
       0 2132.74    13.8 2123.58      27 2113.41    45.9 2099.98    76.3 2081.03
    83.5 2076.09    90.5 2070.48    97.4 2064.03   115.7 2049.34   127.6 2042.04
   129.5 2041.06   135.4 2039.65   147.1 2039.14   155.9 2039.41   162.5 2040.98
   164.7 2041.67   169.9 2043.66   185.7 2044.07   206.6 2043.15   234.5 2042.85
   243.8 2043.91   250.8 2045.57   261.4 2049.91   270.2 2055.69     274 2057.15
   278.7 2058.26   292.6 2068.11   313.5 2081.28   327.5 2089.36   338.7 2098.62
#Mann= 7 ,-1 , 0
       0      .1       0    78.6     .06       0   127.6     .06       0
   129.5    .045       0   162.5     .06       0   164.7     .06       0
  212.48      .1       0
Bank Sta=129.5,162.5
XS Rating Curve= 0 ,0
Exp/Cntr=0.3,0.1

Type RM Length L Ch R = 1 ,2807    ,335.3,344.2,349.6
XS GIS Cut Line= 5
2180664.42721432367484.9435376362180664.42721432367484.943537636
2180794.04758124367592.4465242232180923.66794817367699.949510811
2180923.66794817367699.949510811
#Sta/Elev= 30
       0 2128.17    21.4 2112.68    34.2 2105.02    55.5 2089.49    72.6 2079.92
    84.8    2071   103.5 2060.66   115.2 2052.99   140.8 2042.75   153.6 2033.92
   157.1 2032.21   166.4  2031.5   171.5 2032.12   177.62033.988   183.4 2034.69
   194.3 2034.23     209 2035.93   229.3  2033.9   243.1 2034.25   253.8 2033.75
   275.9 2035.41   292.2 2042.93   301.5 2045.38   306.2 2047.68   308.5  2050.1
   310.3 2052.67   320.6 2069.46   324.1 2073.83   328.3 2077.75   336.8 2083.69
#Mann= 5 ,-1 , 0
       0      .1       0    1.69     .06       0  138.62      .1       0
   153.6    .045       0   177.6      .1       0
Bank Sta=153.6,177.6
XS Rating Curve= 0 ,0
Exp/Cntr=0.3,0.1

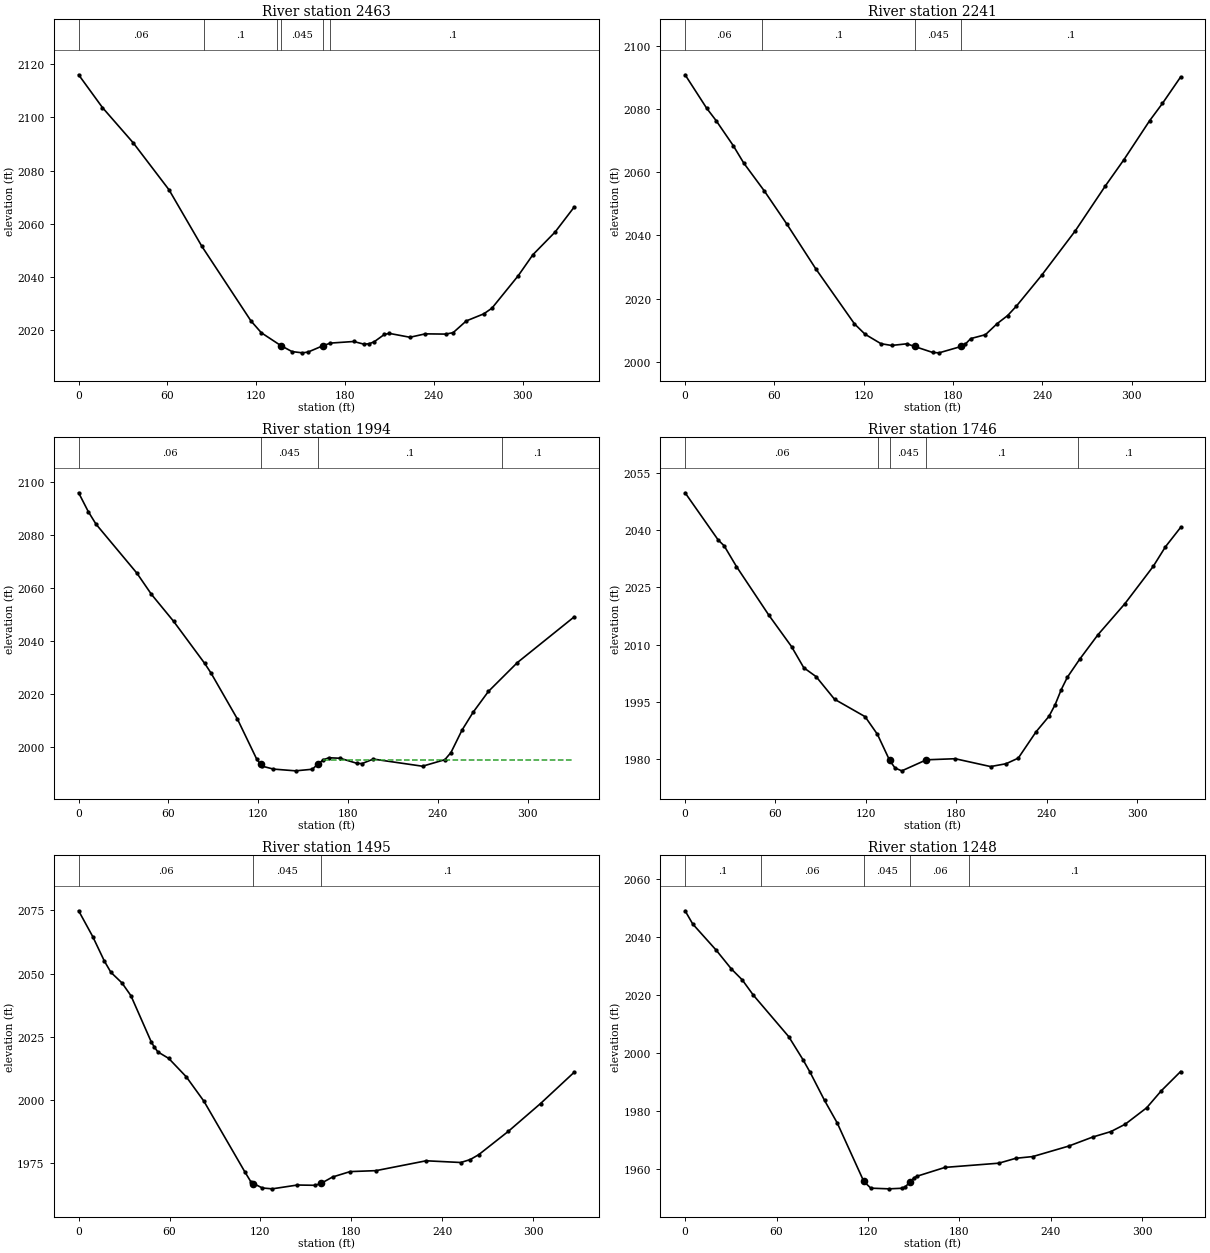
Type RM Length L Ch R = 1 ,2463    ,222.6,221.2,221.6
XS GIS Cut Line= 5
2180500.03493175367595.6186181142180500.03493175367595.618618114
2180553.69994833367754.2355898432180607.36496492367912.852561573
2180607.36496492367912.852561573
#Sta/Elev= 30
       0 2115.95    16.1 2103.64    36.9 2090.39    61.1 2072.74    83.3 2051.51
   116.5 2023.48   123.5 2019.05   136.6 2014.26   144.2 2011.99   151.2 2011.52
     155  2011.8   165.1 2014.19   170.2 2015.18   185.9 2015.78   192.7 2014.79
   196.2 2014.91   199.7 2015.66   206.6 2018.42     210 2018.82   223.9 2017.37
   234.3 2018.65   248.1 2018.56   253.1  2019.1     262 2023.51   273.8 2026.16
   279.3 2028.28   297.1 2040.49     307 2048.37     322 2056.88   334.9 2066.27
#Mann= 6 ,-1 , 0
       0     .06       0   84.66      .1       0   134.3     .06       0
   136.6    .045       0   165.1     .06       0   170.2      .1       0
Bank Sta=136.6,165.1
XS Rating Curve= 0 ,0
Exp/Cntr=0.3,0.1

Type RM Length L Ch R = 1 ,2241    ,248.8,247,243.9
XS GIS Cut Line= 5
2180306.38433323367712.2580485072180306.38433323367712.258048507
2180369.67168803367866.2063876312180432.95904283368020.154726755
2180432.95904283368020.154726755
#Sta/Elev= 30
       0 2090.87    14.5 2080.28    20.8 2076.39    32.3 2068.48    39.4 2062.93
    53.2 2054.12    68.5 2043.51    87.7 2029.52   113.8 2012.02   120.9 2008.75
   131.6 2005.75   138.7  2005.2     149 2005.72   154.22004.873   166.4 2002.97
   170.6 2002.86   185.52004.883   188.3 2005.65   191.9 2007.37   201.8 2008.61
   209.6 2012.09   216.7 2014.67   222.5 2017.61   239.5 2027.39   262.1 2041.46
   282.2 2055.61   294.8    2064     312 2076.29   320.7 2081.82   332.9 2090.18
#Mann= 4 ,-1 , 0
       0     .06       0   51.82      .1       0   154.2    .045       0
   185.5      .1       0
Bank Sta=154.2,185.5
XS Rating Curve= 0 ,0
Exp/Cntr=0.3,0.1

Type RM Length L Ch R = 1 ,1994    ,250.3,248.5,244.5
XS GIS Cut Line= 5
2180069.03103734 367797.434283942180069.03103734 367797.43428394
2180145.89030244367944.0040106862180222.74956753368090.573737431
2180222.74956753368090.573737431
#Sta/Elev= 30
       0 2095.84     6.4 2088.78    11.6 2084.02    38.9 2065.56    48.6 2057.58
    63.5 2047.35    84.2 2031.53    88.4 2027.92   106.1 2010.51     119 1995.39
   121.7 1993.44   122.7 1992.78   130.1 1991.69   144.9 1991.03   156.1 1991.63
   159.8 1993.58   163.5 1995.21   167.2 1995.96   174.6 1995.78   186.2 1993.81
   189.4 1993.79   196.8 1995.46   229.7 1992.77   244.6 1995.23   248.7 1997.93
   256.1 2006.39   263.5 2013.11   273.7 2020.95   293.1 2031.86     331 2049.06
#Mann= 4 ,-1 , 0
       0     .06       0   121.7    .045       0   159.8      .1       0
  283.04      .1       0
#XS Ineff= 2 , 0
                          163.27         1995.24
Permanent Ineff=
       F       F
Bank Sta=121.7,159.8
XS Rating Curve= 0 ,0
Exp/Cntr=0.3,0.1

Type RM Length L Ch R = 1 ,1746    ,248.5,250.7,249.6
XS GIS Cut Line= 5
2179847.53962353367941.0073337292179847.53962353367941.007333729
2179944.85053105368073.6369734812180042.16143856368206.266613233
2180042.16143856368206.266613233
#Sta/Elev= 30
       0 2049.78      22 2037.41    25.9 2035.92    34.1 2030.48    55.6 2017.75
    70.7 2009.51    78.8 2003.99      87 2001.66    99.2 1995.75   119.5 1991.19
   127.7 1986.56   135.8 1979.74   139.4 1977.74   143.9 1977.01   160.2  1979.9
   179.3 1980.18   202.8 1978.13   213.1 1978.87   221.2 1980.34     233 1987.22
   241.6 1991.29   245.7 1994.34   249.7 1998.24   253.8 2001.51   261.9 2006.18
   274.1 2012.63     292 2020.76   310.8 2030.52   318.9 2035.64     329 2040.72
#Mann= 5 ,-1 , 0
       0     .06       0  127.92      .1       0   135.8    .045       0
   160.2      .1       0  260.57      .1       0
Bank Sta=135.8,160.2
XS Rating Curve= 0 ,0
Exp/Cntr=0.3,0.1

Type RM Length L Ch R = 1 ,1495    ,250.8,246.8,236
XS GIS Cut Line= 5
2179668.66756576 368072.113420052179668.66756576 368072.11342005
2179754.89679842 368211.084314422179841.12603108 368350.05520879
2179841.12603108 368350.05520879
#Sta/Elev= 30
       0 2074.85     9.3 2064.65      17 2054.94    21.3  2050.5    28.6 2046.31
    34.5 2041.28    47.9 2023.03    49.9 2020.98    52.3 2019.01    59.5 2016.43
    71.1 2009.13    82.7 1999.51   109.7 1971.57   113.6 1967.73   115.4 1966.94
   121.3 1965.18   127.8 1964.84   144.4 1966.35     156 1966.24   159.9 1966.96
   167.6 1969.52   179.2 1971.66   196.3 1972.04   229.4 1975.94   252.3 1975.26
   258.5 1976.43   264.1 1978.36   283.6 1987.57   304.9 1998.59   327.1 2010.96
#Mann= 3 ,-1 , 0
       0     .06       0   115.4    .045       0   159.9      .1       0
Bank Sta=115.4,159.9
XS Rating Curve= 0 ,0
Exp/Cntr=0.3,0.1

Type RM Length L Ch R = 1 ,1248    ,144.6,140.4,136.9
XS GIS Cut Line= 5
2179453.74876643368264.0583135262179453.74876643368264.058313526
2179585.25877225368359.6808494412179716.76877808368455.303385356
2179716.76877808368455.303385356
#Sta/Elev= 30
       0 2049.11       5 2044.55    20.5 2035.45    30.4    2029    37.5 2025.25
    44.8 2019.96      68 2005.64    77.3 1997.74    82.1 1993.26    91.5 1983.62
    99.9 1975.76   117.3 1955.61   121.9  1953.3   133.8 1953.07   142.2 1953.27
   144.5 1953.78   147.9 1955.56   150.2 1956.89   152.5 1957.48   170.6 1960.48
   205.9 1961.93     217 1963.62   228.2 1964.22   251.7 1967.83   267.6 1970.98
   279.4 1972.84   288.8 1975.38   302.9 1981.06   312.5 1986.94   325.2 1993.59
#Mann= 5 ,-1 , 0
       0      .1       0   49.61     .06       0   117.3    .045       0
   147.9     .06       0  186.03      .1       0
Bank Sta=117.3,147.9
XS Rating Curve= 0 ,0
Exp/Cntr=0.3,0.1

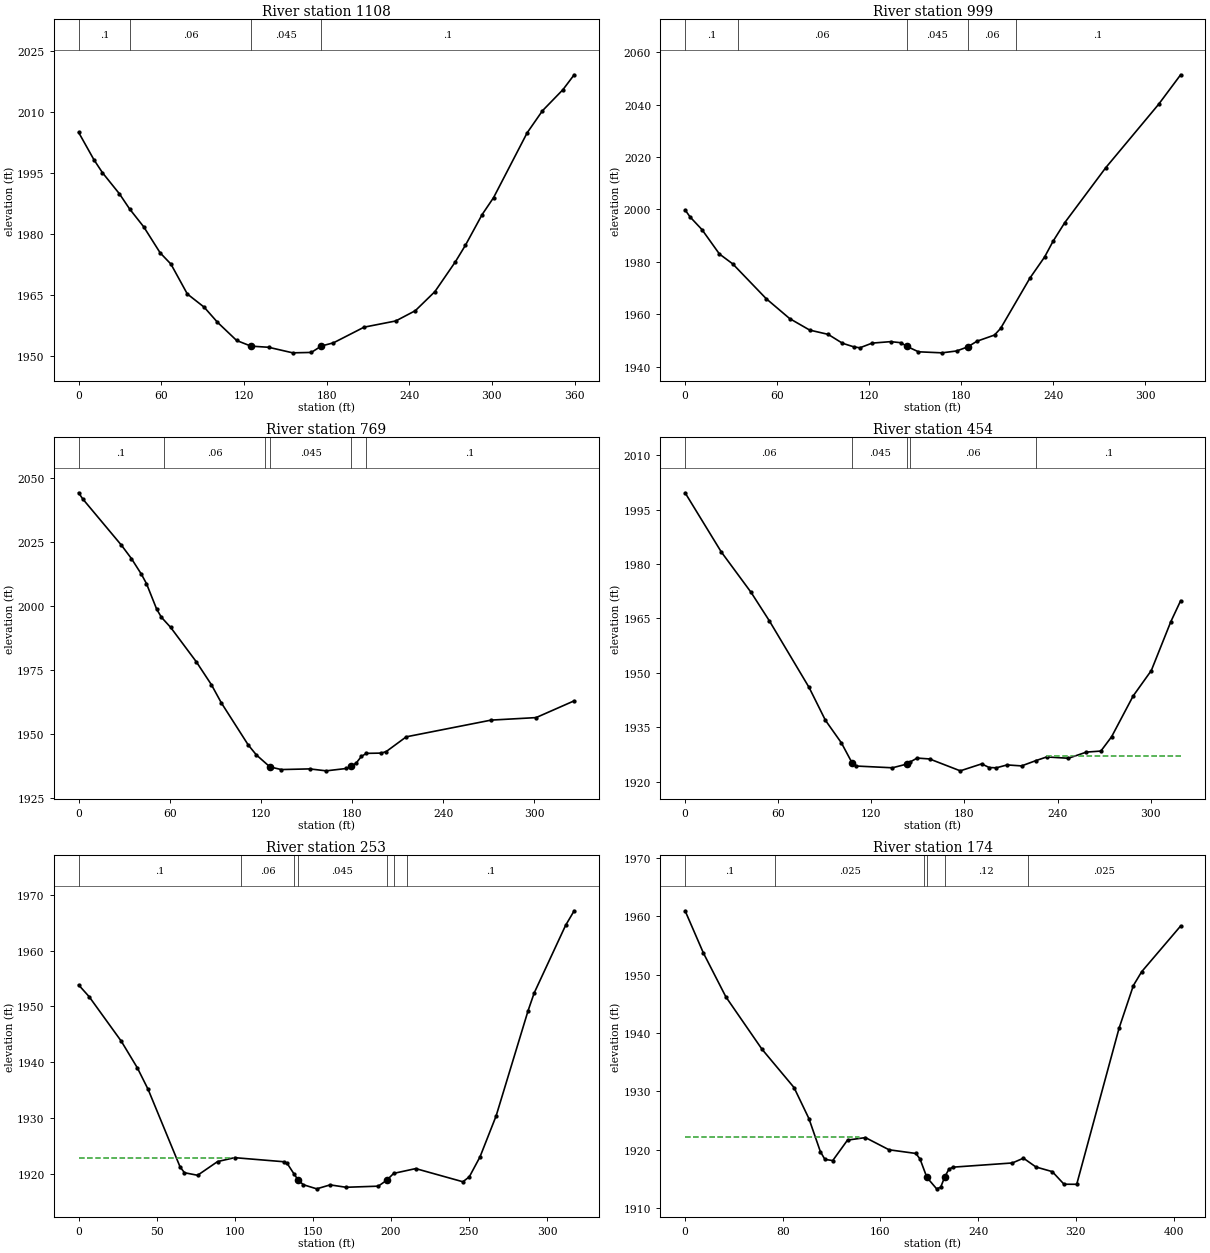
Type RM Length L Ch R = 1 ,1108    ,97,109.2,120.6
XS GIS Cut Line= 2
2179345.59554471368383.7117413442179664.54568686368549.984110531
#Sta/Elev= 30
       0 2005.05    11.1 1998.33    17.3 1995.13    29.6 1989.94      37 1986.21
    47.3 1981.78    59.2 1975.39      67 1972.63    78.9 1965.27    91.1 1962.03
   100.8  1958.3   114.7 1953.82   125.1 1952.43   137.9 1952.15   155.4 1950.78
   168.9 1950.88   176.2 1952.46     185 1953.25   207.2  1957.1   230.2 1958.63
   244.4 1961.16   258.6 1965.85   273.5 1973.21   280.8 1977.29   292.9 1984.83
   301.2    1989   325.6 2004.97   336.7 2010.39   351.5 2015.56   359.7 2019.24
#Mann= 4 ,-1 , 0
       0      .1       0   37.35     .06       0   125.1    .045       0
   176.2      .1       0
Bank Sta=125.1,176.2
XS Rating Curve= 0 ,0
Exp/Cntr=0.3,0.1

Type RM Length L Ch R = 1 ,999     ,220.6,230.3,236.7
XS GIS Cut Line= 5
2179332.16729054368398.6834587122179332.16729054368398.683458712
2179414.76608213368537.5783585822179497.36487371368676.473258452
2179497.36487371368676.473258452
#Sta/Elev= 30
       0 1999.83     3.3 1997.12      11 1992.33    22.4 1983.01    31.1 1979.23
    52.9 1965.97    68.2 1958.38    81.3 1953.98    93.3 1952.36   102.6 1948.98
   110.2 1947.56     114 1947.24     122 1949.02     134 1949.58   140.7 1949.18
   144.6 1947.79   152.2 1945.71   167.5 1945.31   177.1 1946.02   184.3 1947.58
   190.4 1949.75   201.8  1952.1   205.8 1954.65   224.9 1973.83   234.5  1981.9
     240 1987.89   247.6 1994.96   274.3  2015.9   308.8  2040.1   323.2 2051.39
#Mann= 5 ,-1 , 0
       0      .1       0   34.28     .06       0   144.6    .045       0
   184.3     .06       0  215.74      .1       0
Bank Sta=144.6,184.3
XS Rating Curve= 0 ,0
Exp/Cntr=0.3,0.1

Type RM Length L Ch R = 1 ,769     ,323.4,314.5,288.3
XS GIS Cut Line= 4
2179183.96528785368396.3744244272179183.96528785368396.374424427
2179197.59018856368570.5760381492179209.12361292 368721.77141211
#Sta/Elev= 30
       0 2044.31     2.6 2041.98    28.2 2023.79    34.8 2018.55    41.4 2012.39
    44.7 2008.75    51.4 1998.78    54.5 1995.62    60.6 1991.65    77.6 1978.11
    87.5 1969.17      94 1962.11   111.7 1945.65   117.1 1941.72     126 1937.05
   133.5 1936.01   152.2 1936.27   163.1 1935.51   176.3 1936.43   179.6 1937.21
   179.6 1937.23   182.9 1938.61   186.2 1941.13   189.5 1942.35   199.3 1942.45
   202.6 1943.05   215.8 1948.82   271.7 1955.36   301.3 1956.34   326.4  1962.9
#Mann= 6 ,-1 , 0
       0      .1       0   56.07     .06       0   122.9     .06       0
     126    .045       0   179.6     .06       0  189.17      .1       0
Bank Sta=126,179.6
XS Rating Curve= 0 ,0
Exp/Cntr=0.3,0.1

Type RM Length L Ch R = 1 ,454     ,208.4,201.1,191.9
XS GIS Cut Line= 5
2178845.18717502 368618.505348512178845.18717502 368618.50534851
2178961.55851192368727.8014102322179077.92984881368837.097471955
2179077.92984881368837.097471955
#Sta/Elev= 30
       0 1999.61    23.3 1983.31    42.5 1972.16    54.3  1964.3    79.9 1945.93
    90.4  1936.9   100.7 1930.67   107.7 1925.06   110.4 1924.27   133.6 1923.79
   143.1 1924.84   144.8 1925.34   149.5 1926.47   157.5 1926.23   177.3 1922.95
   191.1 1924.87   195.9 1923.87   200.5 1923.78   207.5 1924.58   216.8 1924.31
   226.1 1925.78     233 1926.78     247 1926.42   258.6 1928.12   267.9  1928.4
   274.8 1932.34   288.7 1943.59   300.4  1950.6     313  1964.1   319.3 1969.85
#Mann= 5 ,-1 , 0
       0     .06       0   107.7    .045       0   143.1     .06       0
   144.8     .06       0   226.1      .1       0
#XS Ineff= 2 , 0
                          233.51         1927.03
Permanent Ineff=
       F       F
Bank Sta=107.7,143.1
XS Rating Curve= 0 ,0
Exp/Cntr=0.3,0.1

Type RM Length L Ch R = 1 ,253     ,73,79.4,87.3
XS GIS Cut Line= 2
 2178702.6941075368837.8680476572179006.35782064 368930.18181645
#Sta/Elev= 30
       0 1953.83     6.7 1951.74    27.3 1943.75    37.6 1938.97    44.5 1935.11
      65 1921.19    67.8 1920.16    76.2  1919.7      89 1922.16    99.9 1922.86
   131.4 1922.13   133.6 1921.82   137.8 1920.01   140.5 1918.89   143.9 1918.01
   152.5 1917.27   161.1 1917.98   171.3 1917.55   191.9 1917.75   197.2 1918.78
   201.8 1920.04   215.9  1920.9   246.1 1918.54   250.2 1919.41   257.1 1923.01
   267.4 1930.34   287.9 1949.23   291.8  1952.4   311.9 1964.51   317.4 1967.13
#Mann= 7 ,-1 , 0
       0      .1       0  104.08     .06       0   137.8     .06       0
   140.5    .045       0   197.2     .06       0   201.8     .12       0
   210.3      .1       0
#XS Ineff= 2 , 0
           99.48 1922.87
Permanent Ineff=
       F       F
Bank Sta=140.5,197.2
XS Rating Curve= 0 ,0
Exp/Cntr=0.3,0.1

Type RM Length L Ch R = 1 ,174     ,45.2,41.6,38.3
XS GIS Cut Line= 4
2178633.44785026 368865.79703817  2178772.531027368936.907233797
2178906.38551289368971.4165934392179016.18802084368952.593306362
#Sta/Elev= 30
       0 1960.98      15 1953.73    33.4 1946.21    62.9 1937.25    89.2 1930.66
   101.4 1925.33   110.8 1919.65   114.5 1918.33   120.9 1918.13     133 1921.64
   147.7 1922.07     167 1919.98     189 1919.35   192.4 1918.39     198 1915.24
     206 1913.28   209.3 1913.56   212.7 1915.37   216.1 1916.67   219.5    1917
     268 1917.72   277.1 1918.54   287.3 1917.03   300.7 1916.23   310.3 1914.07
   320.7 1914.06   355.4 1940.85   367.1 1948.16   373.9 1950.53   405.8 1958.37
#Mann= 6 ,-1 , 0
       0      .1       0   74.03    .025       0  195.94     .12       0
     198    .045       0   212.7     .12       0  280.75    .025       0
#XS Ineff= 2 , 0
          142.29 1922.13
Permanent Ineff=
       F       F
Bank Sta=198,212.7
XS Rating Curve= 0 ,0
Exp/Cntr=0.3,0.1

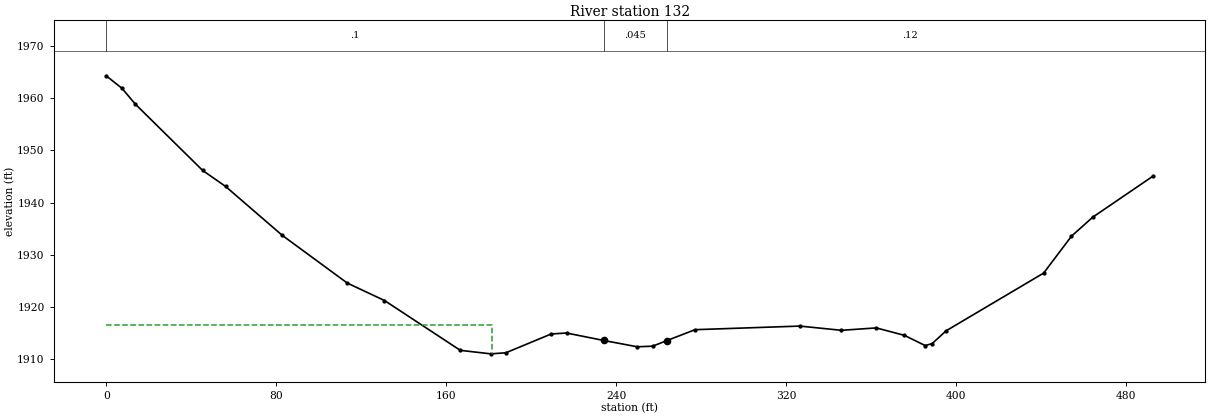
Type RM Length L Ch R = 1 ,132     ,132,132,132
XS GIS Cut Line= 4
 2178572.2849526368876.0855914472178765.07329119368975.881907893
2178818.94062109368987.2223983982179039.51316142 368979.85107957
#Sta/Elev= 30
       0 1964.32     7.5 1961.89    13.7 1958.89    45.4 1946.18    56.2 1943.11
    82.9 1933.73   113.5 1924.59     131 1921.25   166.7  1911.7     181 1911.03
   188.1 1911.23   209.5 1914.84   216.7 1915.02   234.1  1913.6     250 1912.38
   257.2  1912.5   263.9 1913.56   263.9 1913.57   277.2 1915.66   326.5 1916.35
   346.1 1915.54   362.5    1916   375.7 1914.58   385.5 1912.62   388.8 1912.99
   395.4 1915.45   441.3 1926.51   454.4 1933.58   464.3 1937.19   492.8  1945.1
#Mann= 3 , 0 , 0
       0      .1       0   234.1    .045       0   263.9     .12       0
#XS Ineff= 2 , 0
          181.43  1916.5
Permanent Ineff=
       F       F
Bank Sta=234.1,263.9
XS Rating Curve= 0 ,0
Exp/Cntr(USF)=0,0
Exp/Cntr=0.3,0.1
LCMann Table=0

Chan Stop Cuts=-1
Use User Specified Reach Order=0
Composite Channel Slope=5